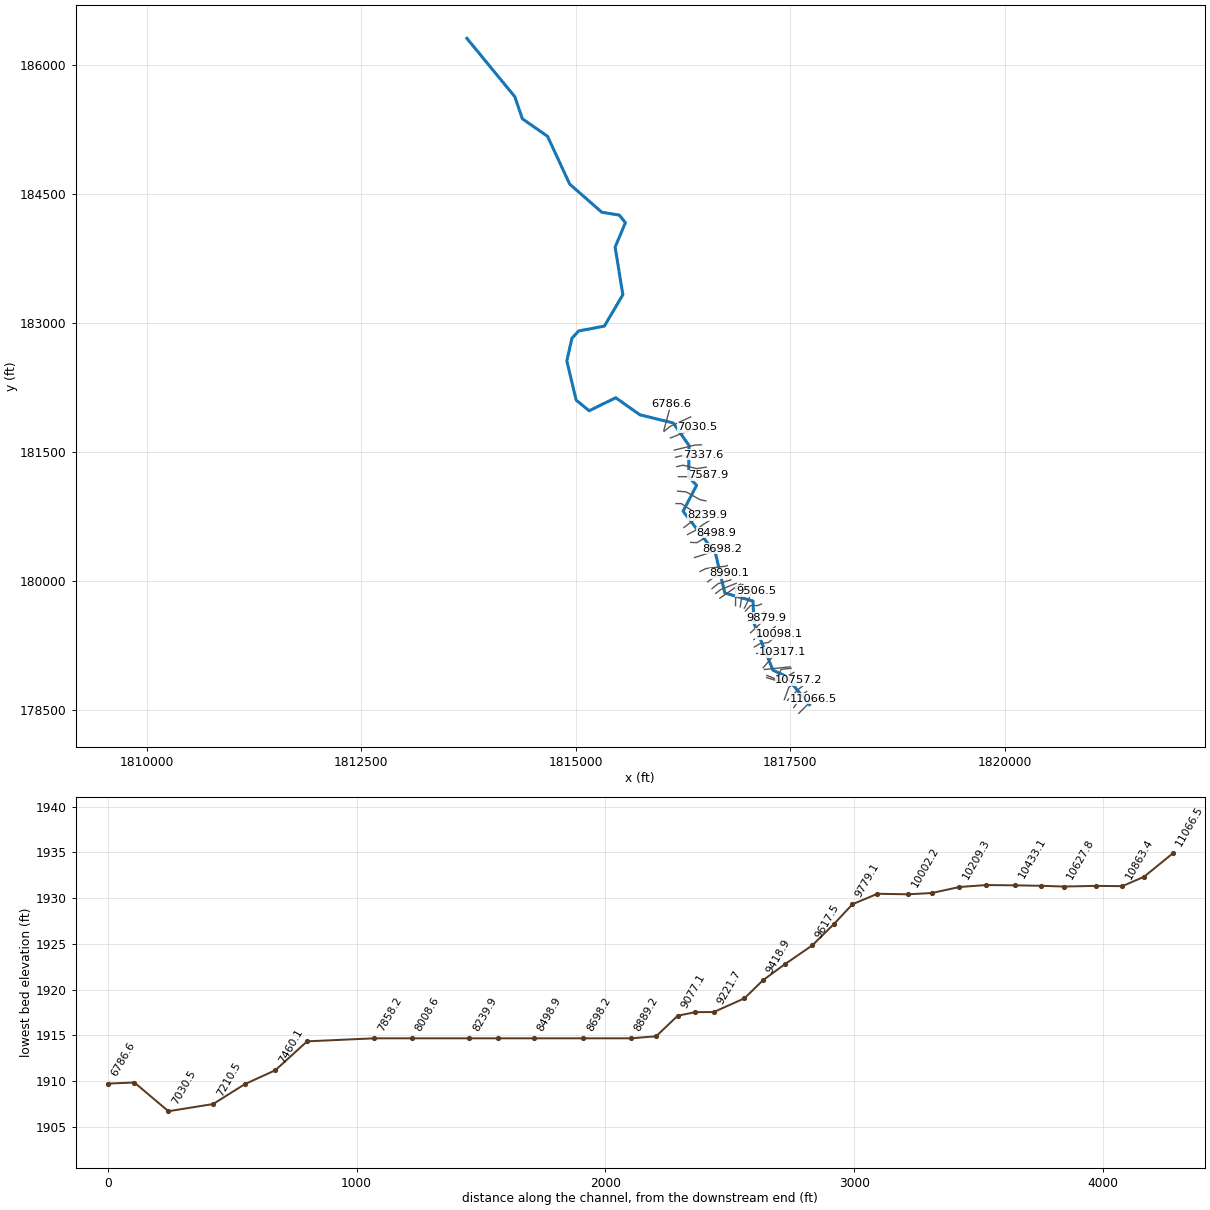
--- HANGINGRN.prj (project) ---

Proj Title=HANGINGRN
Current Plan=p01
Default Exp/Contr=0,0
English Units
Geom File=g01
Flow File=f01
Plan File=p01
BEGIN DESCRIPTION:
END DESCRIPTION:
DSS Export Rating Curves= 0
DSS Export Rating Curve Sorted= 0
DSS Export Volume Flow Curves= 0
DXF OffsetX= 0
DXF OffsetY= 0
DXF ScaleX= 0
DXF ScaleY= 0

--- HANGINGRN.p01 (plan) ---

Plan Title=Floodplain
Program Version=4.00
Geom File=g01
Flow File=f01
K Sum by GR=0
Std Step Tol=0.01
Critical Tol=0.01
Num of Std Step Trials=20
Max Error Tol=0.3
Flow Tol Ratio=0.001
Split Flow NTrial=30
Split Flow Tol=0.02
Split Flow Ratio=0.02
Log Output Level=0
Friction Slope Method=1
Unsteady Friction Slope Method=2
Unsteady Bridges Friction Slope Method=1
Global Log Level=0
CheckData=False
Run HTab=0
Run UNet=0
Run PostProcess=0
UNET Theta=0
UNET Theta Warmup=0
UNET ZTol=0
UNET ZSATol=0
UNET MxIter=0
UNET MaxInSteps=0
UNET DtIC=0
UNET DtMin=0
UNET MaxCRTS=0
UNET WFStab=0
UNET SFStab=0
UNET WFX=0
UNET SFX=0
UNET DSS MLevel=0
UNET DZMax Abort=0
UNET Convert EG Bridges=0
UNET Use Existing IB Tables=0
UNET Froude Limit=0
UNET Froude Power=0
Write IC File=0
Echo Input=False
Echo Output=False
Write Detailed=0

--- HANGINGRN.f01 (steady flow) ---

Flow Title=NFF Regression Equation
Program Version=4.00
Number of Profiles=1
Profile Names=P100yr
River Rch & RM=HANGINGRN,Main      ,11066.5
521.5288
River Rch & RM=HANGINGRN,Main      ,10209.3
563.7122
River Rch & RM=HANGINGRN,Main      ,9879.9
589.1771
River Rch & RM=HANGINGRN,Main      ,6893.7
628.0813
River Rch & RM=HANGINGRN,Main      ,6466.5
718.4071
River Rch & RM=HANGINGRN,Main      ,403.3
790.8663
River Rch & RM=HANGINGRN,Main      ,239.4
1151.543
Boundary for River Rch & Prof#=HANGINGRN,Main      ,1
Up Type=0
Dn Type=3
Dn Slope=0.018815

--- HANGINGRN.g01 (geometry) ---

Geom Title=USGS 10m DEM
Program Version=4.10

River Reach=HANGINGRN       ,Main
Reach XY= 30
     1817723.704      178557.493     1817446.812      178889.076
     1817297.856       178958.95     1817075.953      179506.981
     1817066.082      179763.295     1816737.957      179856.784
     1816628.309      180319.882      1816251.29      180809.427
     1816408.887      181111.162     1816315.658      181205.954
     1816321.149      181573.383     1816135.776      181836.534
     1815747.649      181931.962     1815466.531      182130.331
     1815156.695      181978.727     1815005.609      182102.545
     1814896.396      182558.755     1814956.169      182822.467
     1815034.675      182907.482     1815334.459      182964.163
     1815549.641      183330.143       1815459.1      183882.814
       1815579.1      184167.953     1815508.017      184256.134
     1815304.409      184289.667     1814930.264      184616.808
     1814671.739      185173.994     1814379.169      185377.189
     1814290.278      185634.826     1813732.254      186314.237

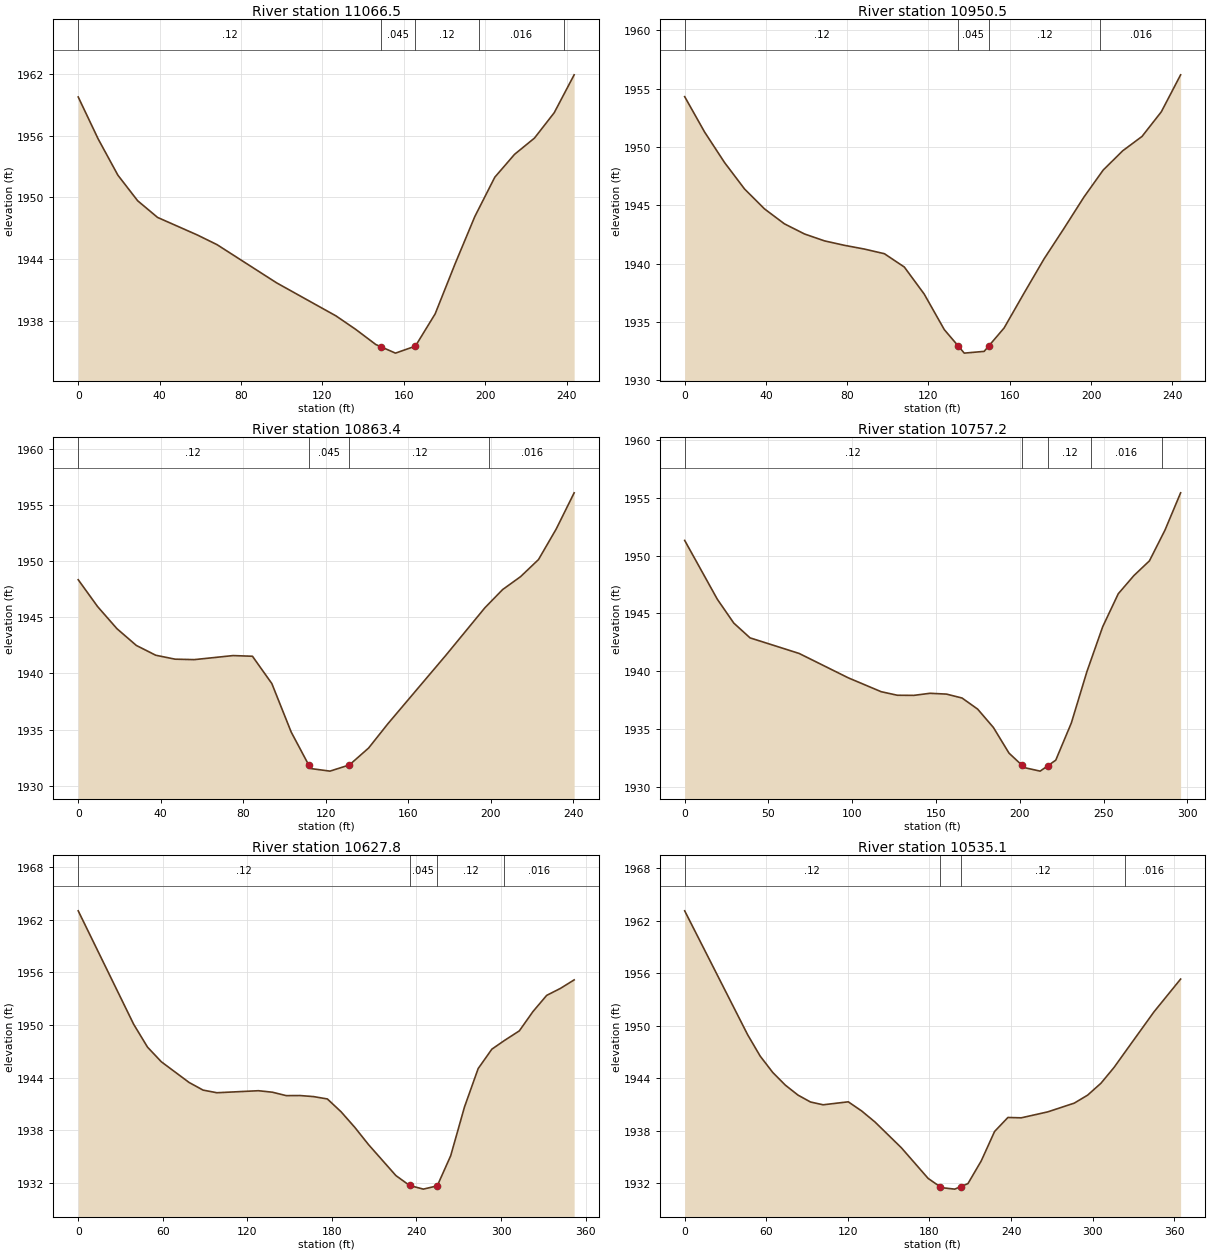
Type RM Length L Ch R = 1 ,11066.5 ,111.6,115.9,120
XS GIS Cut Line= 2
     1817598.705      178455.885     1817772.048      178627.116
#Sta/Elev= 24
       0 1959.75     9.8 1955.68    19.5 1952.16    29.2 1949.68      39 1948.06
    58.5 1946.36    68.2 1945.42    97.5 1941.71   126.7  1938.5   136.4 1937.19
   146.2 1935.73   148.71935.513   155.9 1934.89   165.7 1935.57   175.4  1938.7
   185.2 1943.56   194.9 1948.15  196.761948.873   204.7 1951.96   214.4 1954.18
   224.2 1955.76   233.9 1958.22  238.571959.974   243.7  1961.9
#Mann= 5 ,-1 , 0
       0     .12       0   148.7    .045       0   165.7     .12       0
  196.76    .016       0  238.57     .12       0
Bank Sta=148.7,165.7
XS Rating Curve= 0 ,0
Exp/Cntr=0.3,0.1

Type RM Length L Ch R = 1 ,10950.5 ,91.4,87.2,83
XS GIS Cut Line= 3
     1817540.505      178523.035     1817652.267       178684.71
     1817691.399      178711.668
#Sta/Elev= 29
       0 1954.31     9.8 1951.28    19.6 1948.67    29.5 1946.39    39.3 1944.69
    49.1 1943.41      59 1942.54    68.8 1941.95    78.6 1941.57    88.4 1941.25
    98.3 1940.85   108.1 1939.71   117.9 1937.39   127.8 1934.34   134.6 1932.95
   137.6 1932.33   147.4 1932.48   149.6 1932.93   157.2 1934.48   167.1 1937.49
   176.9 1940.41   186.7 1943.02   196.5  1945.7  204.611947.681     206 1948.02
   215.6 1949.67   225.1  1950.9   234.6 1953.01   244.1 1956.18
#Mann= 4 ,-1 , 0
       0     .12       0   134.6    .045       0   149.6     .12       0
  204.61    .016       0
Bank Sta=134.6,149.6
XS Rating Curve= 0 ,0
Exp/Cntr=0.3,0.1

Type RM Length L Ch R = 1 ,10863.4 ,110.4,106.2,101.8
XS GIS Cut Line= 3
     1817467.473      178608.278     1817607.447      178747.167
      1817643.02      178771.895
#Sta/Elev= 25
       0 1948.34     9.4 1945.95    18.8 1943.98    28.2 1942.49    37.6 1941.62
      47 1941.27    56.3 1941.23    75.1 1941.59    84.5 1941.53    93.9  1939.1
   103.3 1934.78  111.691931.888   112.7 1931.54   122.1 1931.31   131.5 1931.86
   140.8 1933.36   150.2 1935.53   178.4 1941.64   197.2 1945.84  199.43 1946.26
   205.8 1947.46   214.5 1948.61   223.2 1950.13   231.8 1952.85   240.5 1956.07
#Mann= 4 ,-1 , 0
       0     .12       0  111.69    .045       0   131.5     .12       0
  199.43    .016       0
Bank Sta=111.69,131.5
XS Rating Curve= 0 ,0
Exp/Cntr=0.3,0.1

Type RM Length L Ch R = 1 ,10757.2 ,129.8,129.4,127.6
XS GIS Cut Line= 3
     1817430.913      178616.351     1817485.167      178762.835
     1817601.795      178839.794
#Sta/Elev= 30
       0 1951.32    19.5 1946.22    29.3 1944.16      39 1942.88    68.3 1941.53
    97.6 1939.42   117.2 1938.22   126.9 1937.91   136.7  1937.9   146.4 1938.08
   156.2 1938.01   165.5 1937.67   174.8 1936.71   184.2 1935.12   193.5  1932.9
  201.221931.854   202.8 1931.64   212.1 1931.34  216.54 1931.79   221.4 1932.29
   230.7 1935.51     240 1939.96  242.631941.046   249.4 1943.84   258.7  1946.7
     268 1948.27   277.3 1949.55  284.571951.637   286.6 1952.22   295.9 1955.44
#Mann= 5 ,-1 , 0
       0     .12       0  201.22    .045       0  216.54     .12       0
  242.63    .016       0  284.57     .12       0
Bank Sta=201.22,216.54
XS Rating Curve= 0 ,0
Exp/Cntr=0.3,0.1

Type RM Length L Ch R = 1 ,10627.8 ,79.4,92.7,106.2
XS GIS Cut Line= 3
      1817224.75      178872.427     1817365.809      178829.025
     1817541.536      178933.225
#Sta/Elev= 30
       0 1963.03    39.4 1950.07    49.2 1947.47      59  1945.8    78.7 1943.44
    88.6 1942.57    98.4 1942.27   127.9  1942.5   137.8 1942.33   147.6 1941.94
   157.3 1941.95     167 1941.83   176.8 1941.56   186.5  1940.1   196.2 1938.33
     206 1936.35   225.4 1932.82   235.1 1931.69   244.9 1931.27  254.781931.645
   264.3 1935.08   274.1 1940.65   283.8 1945.03   293.5 1947.24  302.411948.232
     313 1949.33   322.7 1951.54   332.4 1953.38   342.2 1954.18   351.9 1955.15
#Mann= 4 ,-1 , 0
       0     .12       0   235.1    .045       0  254.78     .12       0
  302.41    .016       0
Bank Sta=235.1,254.78
XS Rating Curve= 0 ,0
Exp/Cntr=0.3,0.1

Type RM Length L Ch R = 1 ,10535.1 ,125.7,102,78
XS GIS Cut Line= 4
     1817227.672      178897.992     1817339.435      178853.504
     1817393.688      178968.521     1817510.279      178980.533
#Sta/Elev= 30
       0 1963.16    46.3    1949    55.5 1946.56    64.8 1944.68      74 1943.24
    83.3  1942.1    92.5 1941.31   101.8 1940.99   120.3 1941.33   130.1 1940.29
   139.9 1939.03   159.4 1936.07     179 1932.58  187.671931.642   188.8 1931.52
   198.6 1931.35  202.961931.632   208.3 1931.98   218.1 1934.58   227.9 1937.94
   237.7 1939.54   247.5  1939.5     267 1940.18   286.5 1941.18   296.3 1942.09
   306.1 1943.45   315.8 1945.27  323.521946.948   345.1 1951.61   364.7 1955.36
#Mann= 4 ,-1 , 0
       0     .12       0  187.67    .045       0  202.96     .12       0
  323.52    .016       0
Bank Sta=187.67,202.96
XS Rating Curve= 0 ,0
Exp/Cntr=0.3,0.1

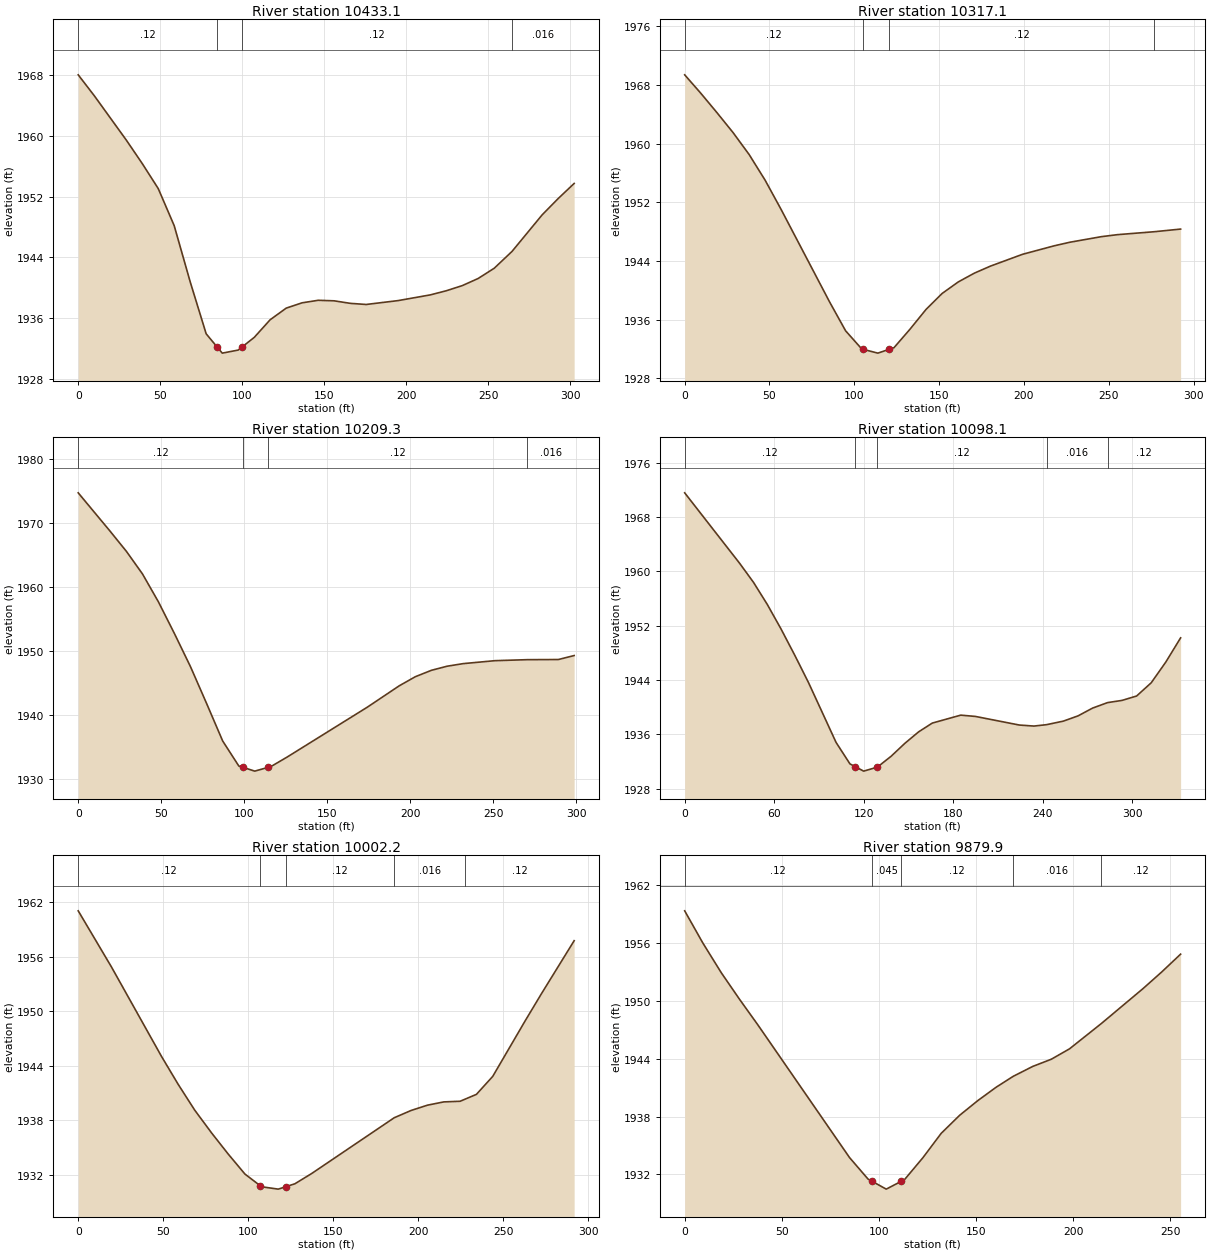
Type RM Length L Ch R = 1 ,10433.1 ,97,115.9,133.5
XS GIS Cut Line= 2
     1817198.708      178966.828     1817499.439      178997.813
#Sta/Elev= 30
       0 1968.01     9.8 1965.26    29.3 1959.43      39 1956.35    48.8 1953.04
    58.5 1948.17    68.3 1940.75      78 1933.94   84.55 1932.24    87.8  1931.4
    97.5  1931.8  100.071932.238   107.3 1933.47     117 1935.79   126.8 1937.32
   136.5 1938.02   146.3 1938.35     156 1938.28   165.8 1937.95   175.5  1937.8
     195 1938.31   214.6 1939.06   224.3  1939.6   234.1 1940.28   243.8 1941.22
   253.6 1942.57   264.41944.772   282.8 1949.59   292.6 1951.74   302.3 1953.72
#Mann= 4 ,-1 , 0
       0     .12       0   84.55    .045       0  100.07     .12       0
   264.4    .016       0
Bank Sta=84.55,100.07
XS Rating Curve= 0 ,0
Exp/Cntr=0.3,0.1

Type RM Length L Ch R = 1 ,10317.1 ,124.8,107.9,90.6
XS GIS Cut Line= 3
     1817184.602      178987.445     1817314.811      179138.269
      1817403.62      179166.392
#Sta/Elev= 27
       0 1969.39     9.5 1966.88      19 1964.24    28.5 1961.52      38 1958.52
    47.4 1955.03    56.9 1951.01    85.4 1938.43    94.9 1934.47   104.4    1932
  105.421931.935   113.9 1931.43  120.331931.934   123.4 1932.17   132.8 1934.68
   142.3 1937.39   151.8 1939.57   161.3 1941.14   170.8 1942.34   180.3  1943.3
   199.2 1944.91   217.9 1946.07   227.2 1946.56   245.8 1947.32   255.2 1947.59
     2771947.992   292.4 1948.35
#Mann= 4 ,-1 , 0
       0     .12       0  105.42    .045       0  120.33     .12       0
     277    .016       0
Bank Sta=105.42,120.33
XS Rating Curve= 0 ,0
Exp/Cntr=0.3,0.1

Type RM Length L Ch R = 1 ,10209.3 ,110.2,111.2,112.2
XS GIS Cut Line= 3
     1817108.647      179152.375     1817319.986      179176.121
     1817401.921      179202.151
#Sta/Elev= 25
       0 1974.66    19.3 1968.64      29 1965.53    38.7    1962    48.3 1957.64
      58 1952.66    67.7 1947.47    77.3 1941.78      87 1935.92    96.7 1932.02
   98.961931.833   106.3 1931.22   114.1 1931.79     116 1931.93   125.7  1933.4
     174 1941.19   193.3 1944.54     203 1945.96   212.7 1946.96   222.2  1947.6
   231.8    1948   250.9 1948.46  270.491948.618   289.1 1948.64   298.6 1949.26
#Mann= 4 ,-1 , 0
       0     .12       0   98.96    .045       0   114.1     .12       0
  270.49    .016       0
Bank Sta=98.96,114.1
XS Rating Curve= 0 ,0
Exp/Cntr=0.3,0.1

Type RM Length L Ch R = 1 ,10098.1 ,88.6,95.9,103
XS GIS Cut Line= 4
     1817081.188      179228.938     1817145.207       179265.83
     1817245.366      179281.498     1817367.317      179380.697
#Sta/Elev= 30
       0 1971.57    36.9 1961.17    46.2 1958.36    55.4 1955.12    64.6 1951.51
    73.9  1947.6    83.1 1943.57   101.5 1934.79   110.8 1931.63  114.41 1931.21
     120 1930.56   129.2 1931.15   138.4 1932.75   147.6 1934.65   156.8 1936.34
     166 1937.64   185.1 1938.81   194.9 1938.62   224.4 1937.35   234.2  1937.2
  242.691937.408   253.9 1937.93   263.7  1938.7   273.5 1939.85  283.551940.658
   293.2 1940.98     303 1941.63   312.8 1943.58   322.6 1946.64   332.5  1950.2
#Mann= 5 ,-1 , 0
       0     .12       0  114.41    .045       0   129.2     .12       0
  242.69    .016       0  283.55     .12       0
Bank Sta=114.41,129.2
XS Rating Curve= 0 ,0
Exp/Cntr=0.3,0.1

Type RM Length L Ch R = 1 ,10002.2 ,115.6,122.3,128.3
XS GIS Cut Line= 3
     1817075.763      179314.658     1817241.778      179399.294
     1817324.285      179465.007
#Sta/Elev= 25
       0 1961.05    19.6 1954.86      49 1945.03    58.8 1941.96    68.6  1939.1
    78.5  1936.6    88.3 1934.27    98.1 1932.08   107.2 1930.78   107.9 1930.68
   117.7 1930.42   122.2 1930.69   127.5 1931.01   137.3 1932.13  185.97 1938.28
   195.9 1939.08   205.5 1939.66   215.1 1940.02   224.7 1940.09  227.781940.334
   234.3 1940.85   243.9 1942.83   263.1 1948.98   272.6 1951.94   291.8 1957.76
#Mann= 5 ,-1 , 0
       0     .12       0   107.2    .045       0   122.2     .12       0
  185.97    .016       0  227.78     .12       0
Bank Sta=107.2,122.2
XS Rating Curve= 0 ,0
Exp/Cntr=0.3,0.1

Type RM Length L Ch R = 1 ,9879.9  ,118.6,100.8,82.8
XS GIS Cut Line= 3
     1817037.033      179394.346     1817203.049      179548.426
     1817225.937      179566.014
#Sta/Elev= 24
       0 1959.32     9.4 1955.97    18.9 1952.89    28.3 1950.14    37.8 1947.47
    84.9 1933.75    94.4 1931.53   96.391931.304   103.8 1930.48  111.451931.281
   113.2 1931.46   122.7 1933.74   132.1 1936.26   141.6 1938.13     151 1939.66
   160.4 1941.04  169.231942.174   179.3  1943.2   188.8 1943.94   198.2 1945.02
  214.581947.641   236.1 1951.27   245.7 1952.99   255.4 1954.83
#Mann= 5 ,-1 , 0
       0     .12       0   96.39    .045       0  111.45     .12       0
  169.23    .016       0  214.58     .12       0
Bank Sta=96.39,111.45
XS Rating Curve= 0 ,0
Exp/Cntr=0.3,0.1

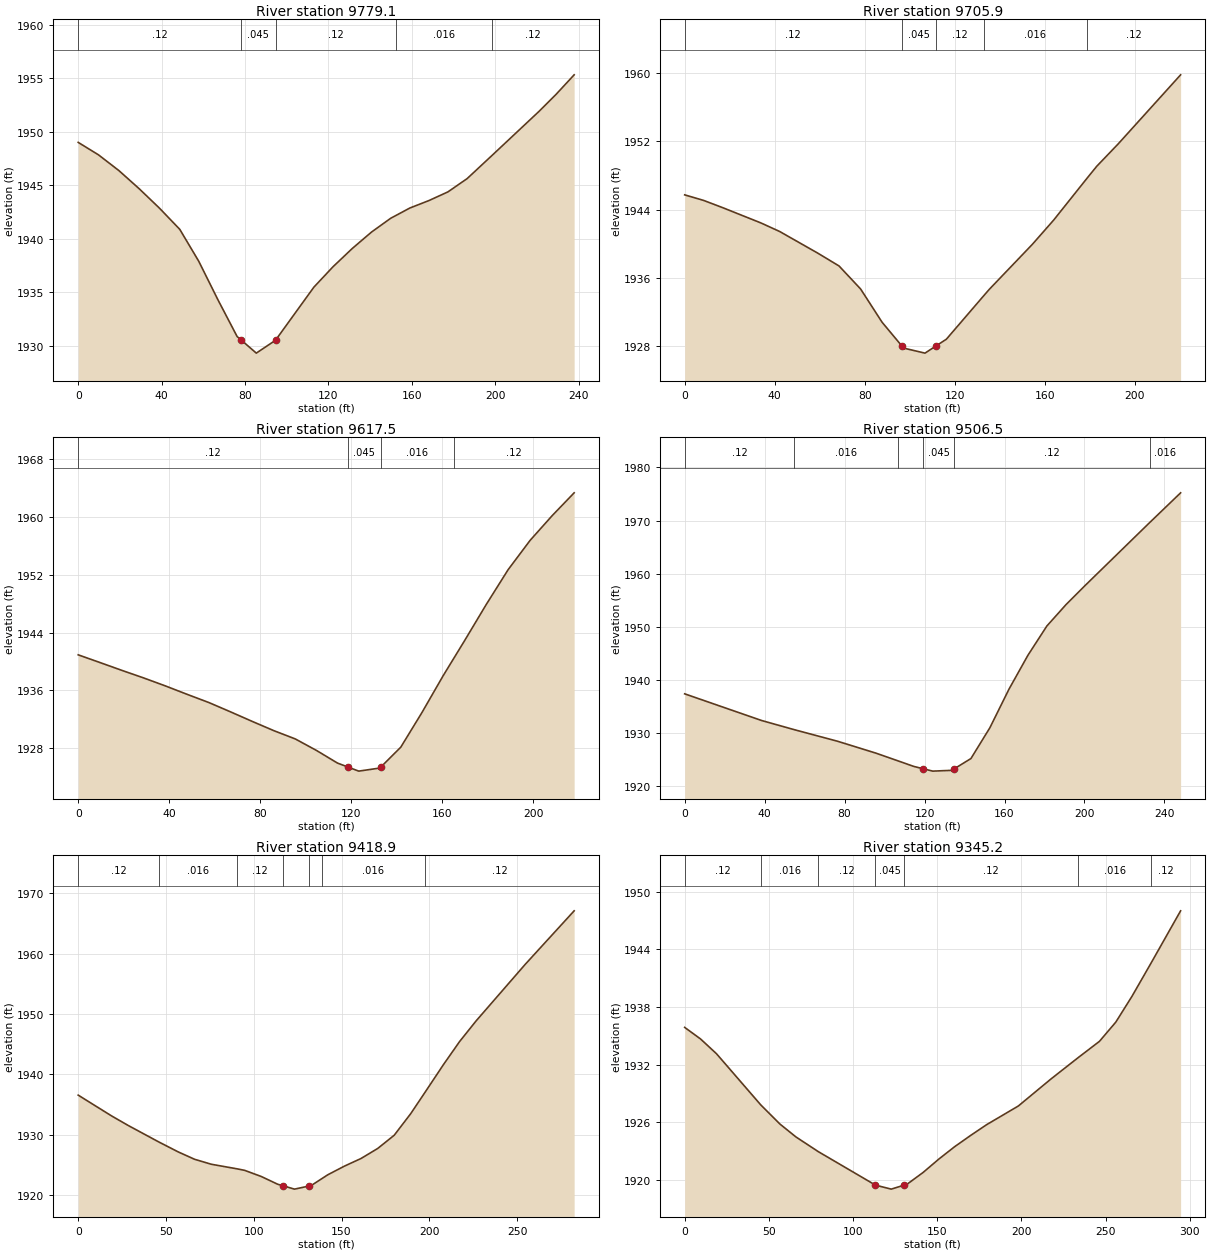
Type RM Length L Ch R = 1 ,9779.1  ,73.2,73.1,72.8
XS GIS Cut Line= 4
     1816999.213      179525.592     1817040.288      179551.681
     1817178.092       179547.34     1817220.016      179576.842
#Sta/Elev= 26
       0 1949.01     9.7 1947.85    19.5 1946.38    29.2 1944.69    38.9 1942.88
    48.7 1940.89    57.8 1937.91      67 1934.31    76.2 1930.88   78.121930.557
    85.4 1929.33    94.6 1930.53     113 1935.49   122.2  1937.4   131.4  1939.1
   140.6 1940.63   149.8 1941.92   152.41942.191     159 1942.88   168.2 1943.58
   177.3 1944.39   186.5 1945.63  198.471947.801   220.7 1951.86   229.2 1953.51
   237.8 1955.32
#Mann= 5 ,-1 , 0
       0     .12       0   78.12    .045       0    94.6     .12       0
   152.4    .016       0  198.47     .12       0
Bank Sta=78.12,94.6
XS Rating Curve= 0 ,0
Exp/Cntr=0.3,0.1

Type RM Length L Ch R = 1 ,9705.9  ,86.9,88.4,89.4
XS GIS Cut Line= 4
     1816992.097      179587.513     1817037.785      179624.988
     1817171.249      179619.563     1817195.271      179633.402
#Sta/Elev= 22
       0 1945.74     8.4 1945.09    16.9 1944.24    33.8 1942.46    42.2 1941.45
    59.1 1938.92    68.6 1937.41    78.2 1934.71    87.7 1930.83   96.581928.018
    97.3 1927.79   106.8  1927.2  111.531928.014   116.3 1928.83  133.041933.965
   135.4 1934.68   154.5 1939.94     164 1942.79  178.621947.623   183.1 1949.08
   192.7 1951.72   220.4  1959.8
#Mann= 5 ,-1 , 0
       0     .12       0   96.58    .045       0  111.53     .12       0
  133.04    .016       0  178.62     .12       0
Bank Sta=96.58,111.53
XS Rating Curve= 0 ,0
Exp/Cntr=0.3,0.1

Type RM Length L Ch R = 1 ,9617.5  ,85.2,111,136.4
XS GIS Cut Line= 4
     1816977.422      179646.914     1817035.948      179710.101
     1817119.498      179711.186     1817164.619      179728.609
#Sta/Elev= 30
       0 1940.93     9.6 1939.86    19.1 1938.79    28.7 1937.74    38.3 1936.63
    47.8 1935.47    57.4 1934.33      67 1933.03    76.6  1931.7    86.1 1930.42
    95.4 1929.29   104.7  1927.7     114 1925.94   117.2 1925.56  118.62 1925.39
  122.951924.872   123.3 1924.83   132.2 1925.24   132.6 1925.26  132.95 1925.37
   141.8 1928.15   151.1 1932.94   160.4 1938.03   165.11940.451   169.7 1942.82
   179.4 1947.92     189 1952.73   198.7  1956.8   208.4 1960.22     218 1963.36
#Mann= 4 ,-1 , 0
       0     .12       0  118.62    .045       0  132.95    .016       0
   165.1     .12       0
Bank Sta=118.62,132.95
XS Rating Curve= 0 ,0
Exp/Cntr=0.3,0.1

Type RM Length L Ch R = 1 ,9506.5  ,81.3,87.6,93.7
XS GIS Cut Line= 4
     1816963.515      179680.847     1816970.467      179687.942
     1817038.118      179834.884     1817099.101      179880.849
#Sta/Elev= 20
       0 1937.33    38.5  1932.3   54.891930.568    76.5 1928.39    95.6 1926.16
  106.871924.675   114.6 1923.65  119.091923.228   124.1 1922.76   133.6 1922.91
   134.91923.208   143.2 1925.13   152.7 1930.95   162.2 1938.18   171.7 1944.59
   181.2 1950.12   190.8 1954.16   200.3 1957.74  232.561969.592   248.1 1975.22
#Mann= 6 ,-1 , 0
       0     .12       0   54.89    .016       0  106.87     .12       0
  119.09    .045       0   134.9     .12       0  232.56    .016       0
Bank Sta=119.09,134.9
XS Rating Curve= 0 ,0
Exp/Cntr=0.3,0.1

Type RM Length L Ch R = 1 ,9418.9  ,70.1,73.7,77.2
XS GIS Cut Line= 3
      1816916.26      179696.901     1816945.554      179874.554
     1817031.122      179930.951
#Sta/Elev= 28
       0 1936.57      19 1933.13    28.4 1931.56   45.851928.828    56.9 1927.18
    66.3 1925.95    75.8 1925.13   90.591924.364    94.8 1924.12   104.2 1923.11
   113.7 1921.81   116.6 1921.57   123.2 1921.01   131.6 1921.53   132.7  1921.6
  138.59 1922.71   142.2 1923.39   151.6 1924.81   161.1 1926.08   170.6 1927.74
     180 1929.93   189.4  1933.5  197.681937.088     208  1941.6   217.3 1945.46
   226.6 1948.84   254.6 1958.21   282.5 1967.08
#Mann= 7 ,-1 , 0
       0     .12       0   45.85    .016       0   90.59     .12       0
   116.6    .045       0   131.6     .12       0  138.59    .016       0
  197.68     .12       0
Bank Sta=116.6,131.6
XS Rating Curve= 0 ,0
Exp/Cntr=0.3,0.1

Type RM Length L Ch R = 1 ,9345.2  ,145.4,123.5,101.1
XS GIS Cut Line= 3
     1816862.318      179709.393      1816864.29      179907.584
     1816947.204      179956.852
#Sta/Elev= 24
       0 1935.88     9.4 1934.68    18.9 1933.14   45.18 1927.82    56.6 1925.82
    66.1 1924.48   79.411922.948   113.3 1919.47   122.7 1919.05  130.021919.446
   132.1 1919.56   141.6 1920.78     151 1922.18   160.4 1923.47   169.9 1924.64
   179.3 1925.75   198.2  1927.7   217.5  1930.5  233.661932.722   246.4 1934.43
   256.1 1936.43   265.7 1939.11  277.121942.597   294.6 1948.01
#Mann= 7 ,-1 , 0
       0     .12       0   45.18    .016       0   79.41     .12       0
   113.3    .045       0  130.02     .12       0  233.66    .016       0
  277.12     .12       0
Bank Sta=113.3,130.02
XS Rating Curve= 0 ,0
Exp/Cntr=0.3,0.1

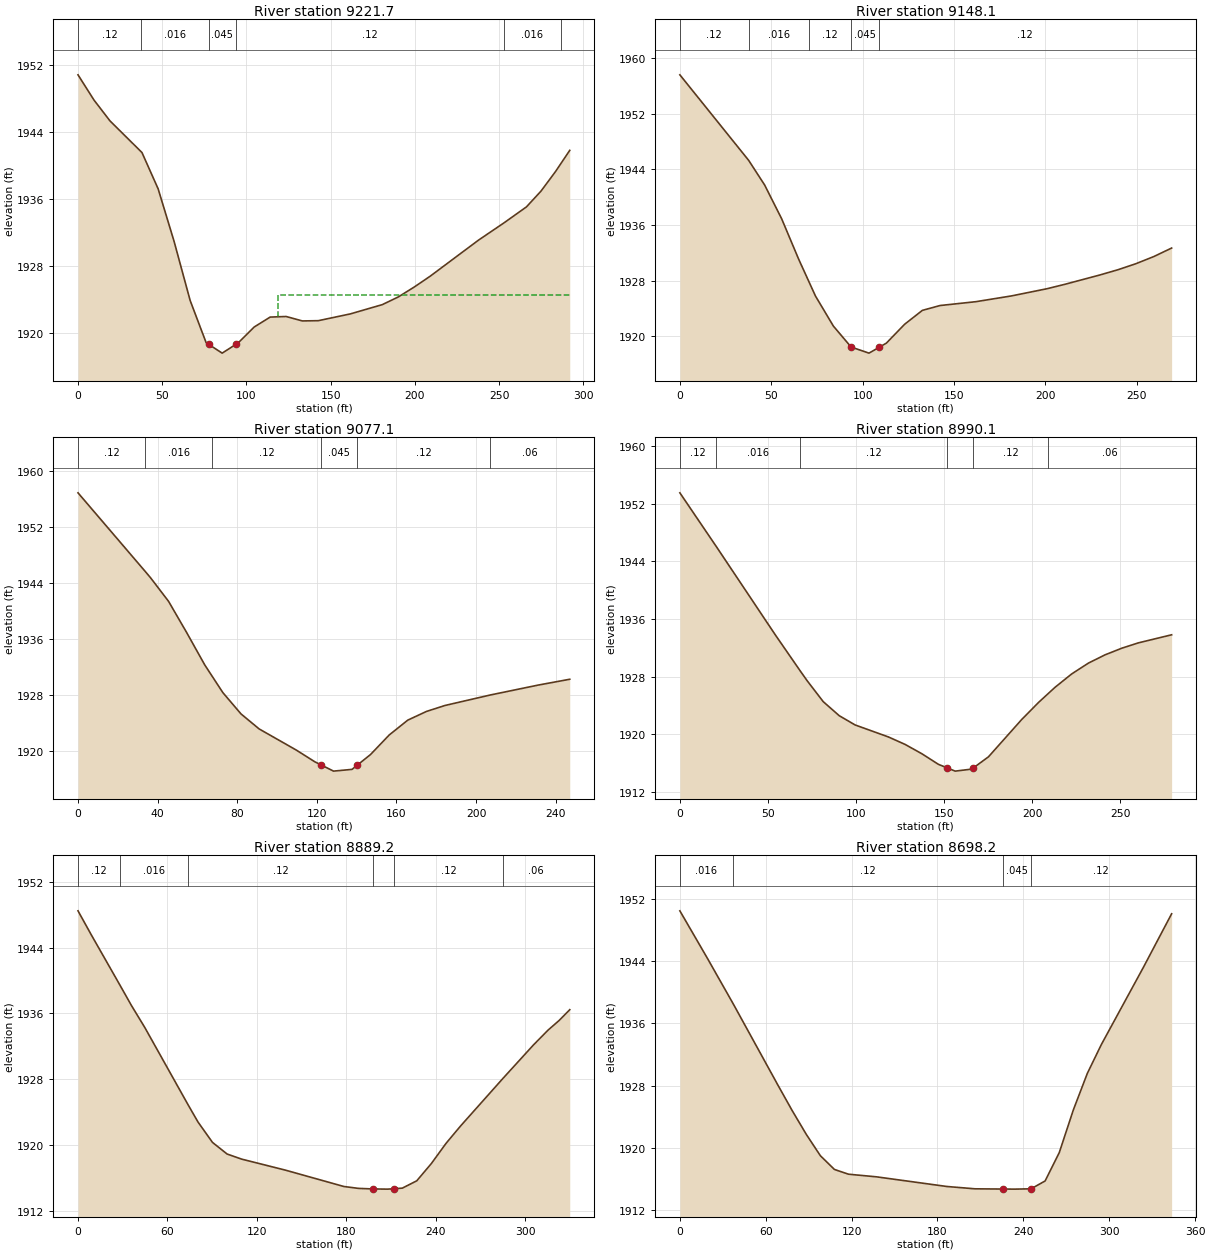
Type RM Length L Ch R = 1 ,9221.7  ,78.8,73.6,68.3
XS GIS Cut Line= 3
     1816679.495      179796.646     1816898.245      179948.556
     1816920.728      179961.046
#Sta/Elev= 30
       0 1950.83     9.5 1947.81      19 1945.32   37.641941.604      38 1941.53
    47.6 1937.19    57.1 1930.88    66.6 1923.84    76.1 1918.79   77.561918.604
    85.6 1917.55   93.93 1918.62    95.1 1918.77   104.6 1920.67   114.1 1921.86
   123.6 1921.93   133.2  1921.4   142.7 1921.43   161.7 1922.24   180.7 1923.35
   190.2 1924.27   199.7 1925.46   209.2 1926.76   237.8 1931.06  252.941933.126
   266.3 1935.04   274.9 1936.92   283.5 1939.25  286.781940.234     292  1941.8
#Mann= 6 ,-1 , 0
       0     .12       0   37.64    .016       0   77.56    .045       0
   93.93     .12       0  252.94    .016       0  286.78     .12       0
#XS Ineff= 2 , 0
                          118.58         1924.53
Permanent Ineff=
       F       F
Bank Sta=77.56,93.93
XS Rating Curve= 0 ,0
Exp/Cntr=0.3,0.1

Type RM Length L Ch R = 1 ,9148.1  ,73,71,68.8
XS GIS Cut Line= 3
     1816631.217      179852.245     1816689.801      179897.842
     1816870.858      179969.877
#Sta/Elev= 24
       0 1957.64   37.661945.312    46.4 1941.76    55.7  1936.9      65 1931.08
   70.651927.819    74.2 1925.77      84 1921.44    93.7 1918.42   103.5 1917.54
  108.981918.371     113 1918.98     123  1921.7   132.7  1923.7   142.4  1924.4
   161.9 1924.95   181.4 1925.78   200.9 1926.82   210.6 1927.45   230.1 1928.82
   239.9 1929.57   249.6 1930.43   259.4 1931.46   269.1 1932.68
#Mann= 5 ,-1 , 0
       0     .12       0   37.66    .016       0   70.65     .12       0
    93.7    .045       0  108.98     .12       0
Bank Sta=93.7,108.98
XS Rating Curve= 0 ,0
Exp/Cntr=0.3,0.1

Type RM Length L Ch R = 1 ,9077.1  ,88.2,86.9,85.3
XS GIS Cut Line= 4
     1816588.248      179908.018     1816658.778      179965.526
     1816793.211      180004.979      1816807.94      180011.117
#Sta/Elev= 24
       0 1956.83   33.671945.658    36.4 1944.74    45.5 1941.36    54.6 1936.91
    63.7 1932.29   67.57 1930.61    72.8 1928.34    81.9 1925.31      91 1923.17
   109.7 1920.15     119 1918.48  122.151918.034   128.4 1917.15   137.7  1917.4
  140.341918.002     147 1919.52   156.4 1922.31   165.7 1924.42   175.1 1925.66
   184.4 1926.51  207.09    1928   231.1 1929.41   247.1 1930.25
#Mann= 6 ,-1 , 0
       0     .12       0   33.67    .016       0   67.57     .12       0
  122.15    .045       0  140.34     .12       0  207.09     .06       0
Bank Sta=122.15,140.34
XS Rating Curve= 0 ,0
Exp/Cntr=0.3,0.1

Type RM Length L Ch R = 1 ,8990.1  ,103.3,100.9,98.6
XS GIS Cut Line= 3
     1816538.002      179985.882     1816616.127      180047.514
     1816791.548      180086.664
#Sta/Elev= 27
       0 1953.48   20.781945.999    54.3 1933.75   68.311928.801    72.4 1927.39
    81.4 1924.53    90.5 1922.58    99.5  1921.3   118.4 1919.64   127.9  1918.6
   137.4 1917.31   146.8 1915.84   151.7 1915.36   156.3  1914.9   165.7 1915.18
   166.7 1915.36   175.2 1916.88   194.1 1922.06   203.6 1924.41  208.861925.591
     213 1926.52   222.5 1928.38     232 1929.88   241.4 1931.02   250.9 1931.94
   260.3 1932.68   279.2  1933.8
#Mann= 6 ,-1 , 0
       0     .12       0   20.78    .016       0   68.31     .12       0
   151.7    .045       0   166.7     .12       0  208.86     .06       0
Bank Sta=151.7,166.7
XS Rating Curve= 0 ,0
Exp/Cntr=0.3,0.1

Type RM Length L Ch R = 1 ,8889.2  ,186.4,191.1,195.1
XS GIS Cut Line= 4
     1816449.021      180108.367     1816521.625      180143.044
     1816754.915       180170.17     1816766.482       180178.95
#Sta/Elev= 26
       0 1948.46     8.9 1945.55    28.2 1939.42    35.8 1936.98    44.7 1934.33
   73.911924.892    80.5 1922.82    90.2 1920.35     100 1918.94   109.8 1918.32
   139.2 1916.98   178.3    1915   188.1 1914.77   197.9  1914.7   207.7 1914.68
  212.141914.731   217.5  1914.8   227.2 1915.69     237 1917.79   246.8 1920.23
   256.6 1922.35   284.8 1928.08   305.5 1932.19   315.3 1933.99   322.6 1935.14
   329.8 1936.46
#Mann= 6 ,-1 , 0
       0     .12       0    28.2    .016       0   73.91     .12       0
   197.9    .045       0  212.14     .12       0   284.8     .06       0
Bank Sta=197.9,212.14
XS Rating Curve= 0 ,0
Exp/Cntr=0.3,0.1

Type RM Length L Ch R = 1 ,8698.2  ,193.4,199.3,204.4
XS GIS Cut Line= 2
     1816384.289      180269.831     1816711.629      180374.317
#Sta/Elev= 22
       0 1950.46    19.6 1944.24   37.181938.534    68.7 1927.99    78.5 1924.77
    88.4  1921.7    98.2 1918.97     108 1917.21   117.8  1916.6   137.4 1916.26
   186.5 1915.02   206.2 1914.72   225.8 1914.69   234.1 1914.68   245.4 1914.72
   255.2 1915.73   265.1 1919.38   274.9 1924.85   284.7 1929.56   294.5 1933.27
     324 1943.24   343.6 1950.08
#Mann= 4 ,-1 , 0
       0    .016       0   37.18     .12       0   225.8    .045       0
   245.4     .12       0
Bank Sta=225.8,245.4
XS Rating Curve= 0 ,0
Exp/Cntr=0.3,0.1

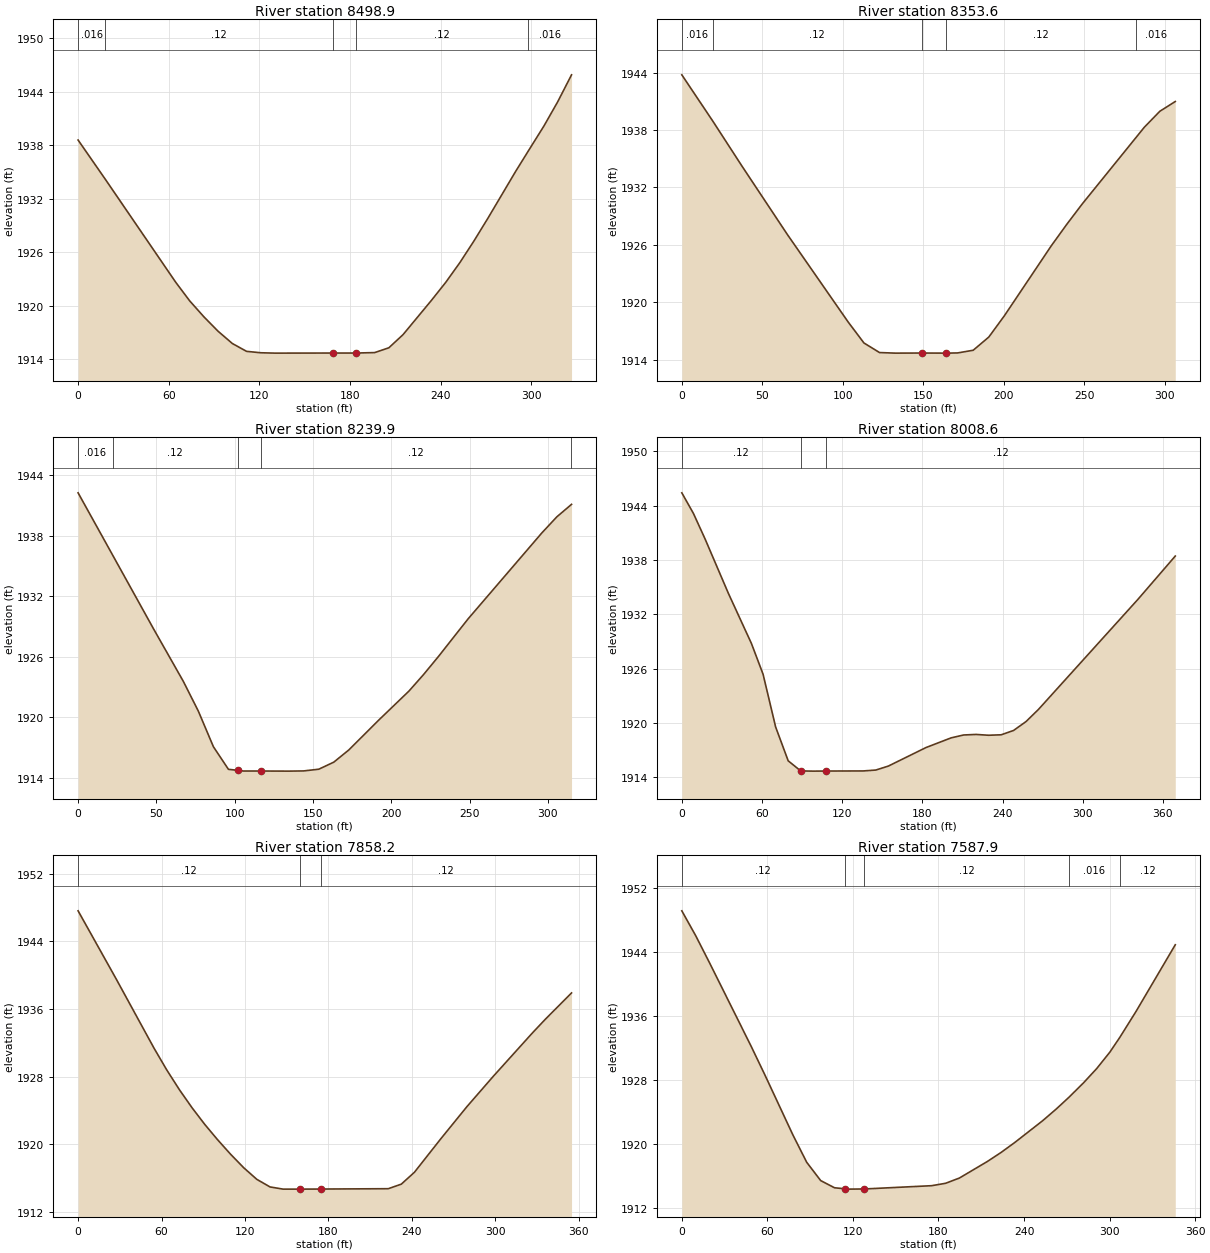
Type RM Length L Ch R = 1 ,8498.9  ,144.1,145.3,146.7
XS GIS Cut Line= 4
     1816339.869      180446.386     1816413.653       180443.13
     1816557.968      180532.106     1816636.676      180559.247
#Sta/Elev= 25
       0  1938.6   18.121934.172    64.6 1922.64    73.9 1920.54    83.3 1918.75
    92.7 1917.13   102.1 1915.76   111.5 1914.88     121 1914.72   130.4 1914.68
   168.7 1914.69   183.7 1914.69   196.3 1914.74   205.7 1915.28   215.1 1916.76
     234 1920.63   243.4 1922.64   252.6 1924.82   261.9 1927.24   271.2 1929.81
   289.6 1935.08   297.71937.292   308.2 1940.14   317.4 1942.88   326.6 1945.92
#Mann= 5 ,-1 , 0
       0    .016       0   18.12     .12       0   168.7    .045       0
   183.7     .12       0   297.7    .016       0
Bank Sta=168.7,183.7
XS Rating Curve= 0 ,0
Exp/Cntr=0.3,0.1

Type RM Length L Ch R = 1 ,8353.6  ,112.6,113.8,114.3
XS GIS Cut Line= 4
     1816302.759      180537.965     1816386.234      180580.614
     1816495.468      180661.446     1816561.174      180701.766
#Sta/Elev= 21
       0 1943.77   19.351938.907    37.5  1934.2    65.6 1927.08   103.4 1917.93
   113.2 1915.74   122.9 1914.74   132.6 1914.68   149.1 1914.69   164.1 1914.68
   171.4  1914.7   181.1 1914.98   190.8 1916.36   200.5 1918.59   229.6 1925.89
   239.3 1928.15   248.9 1930.28  282.421937.243   287.4 1938.28   297.1 1939.96
   306.7 1940.98
#Mann= 5 ,-1 , 0
       0    .016       0   19.35     .12       0   149.1    .045       0
   164.1     .12       0  282.42    .016       0
Bank Sta=149.1,164.1
XS Rating Curve= 0 ,0
Exp/Cntr=0.3,0.1

Type RM Length L Ch R = 1 ,8239.9  ,259,231.2,203.4
XS GIS Cut Line= 3
     1816260.644      180619.259     1816429.047      180746.863
     1816532.102      180759.482
#Sta/Elev= 24
       0 1942.24   21.981936.097      48 1928.82    67.2 1923.57    76.8 1920.62
    86.4  1917.1      96 1914.86  101.871914.758   105.6 1914.69  116.81 1914.69
   134.5 1914.68   144.1  1914.7   153.7 1914.87   163.3 1915.57   172.9 1916.78
   192.1 1919.75   211.3 1922.61   220.7 1924.26   230.2 1926.05     249 1929.75
   296.2 1938.28   305.7 1939.86  314.72 1941.05   315.1  1941.1
#Mann= 5 ,-1 , 0
       0    .016       0   21.98     .12       0  101.87    .045       0
  116.81     .12       0  314.72    .016       0
Bank Sta=101.87,116.81
XS Rating Curve= 0 ,0
Exp/Cntr=0.3,0.1

Type RM Length L Ch R = 1 ,8008.6  ,148.7,150.5,151.9
XS GIS Cut Line= 4
     1816168.567      180898.407     1816229.394      180897.905
       1816378.7      180800.682     1816508.517      180812.095
#Sta/Elev= 25
       0  1945.4     8.7 1943.12    17.4 1940.31    34.8 1934.32    52.1 1928.77
    60.8 1925.38    70.2 1919.56    79.6 1915.82      89  1914.7    98.3 1914.68
   107.7 1914.69   135.8  1914.7   145.2  1914.8   154.6 1915.24   182.7 1917.28
   201.5 1918.35   210.9 1918.67   220.2 1918.73   229.6 1918.64     239 1918.69
   248.3 1919.17   257.6 1920.15   266.9 1921.49   341.4 1933.65   369.3 1938.42
#Mann= 3 ,-1 , 0
       0     .12       0      89    .045       0   107.7     .12       0
Bank Sta=89,107.7
XS Rating Curve= 0 ,0
Exp/Cntr=0.3,0.1

Type RM Length L Ch R = 1 ,7858.2  ,258.2,270.3,281.7
XS GIS Cut Line= 4
     1816186.859       181042.87     1816286.686      181034.189
     1816451.616      180942.176     1816516.241      180930.018
#Sta/Elev= 24
       0 1947.63    27.3 1939.59    54.7 1931.34    63.8 1928.78    72.9 1926.44
      82  1924.3    91.1 1922.34   100.2 1920.55   109.6 1918.82   119.1 1917.21
   128.5 1915.84     138 1914.94   147.4 1914.68   159.7 1914.68   174.7 1914.69
     223 1914.73   232.4 1915.27   241.8 1916.67   260.7 1920.62   279.6 1924.45
   298.5 1928.03   326.6 1933.16     336  1934.8   354.8 1937.91
#Mann= 3 ,-1 , 0
       0     .12       0   159.7    .045       0   174.7     .12       0
Bank Sta=159.7,174.7
XS Rating Curve= 0 ,0
Exp/Cntr=0.3,0.1

Type RM Length L Ch R = 1 ,7587.9  ,133.8,127.8,120.8
XS GIS Cut Line= 3
     1816197.276      181211.273     1816469.845      181212.141
      1816541.26      181229.702
#Sta/Elev= 27
       0  1949.2     9.7  1946.1    19.5 1942.67    48.7 1932.21    58.4  1928.6
    77.9 1921.14    87.6 1917.71    97.4 1915.42   107.1 1914.52   114.11914.398
   116.8 1914.35  128.05 1914.37   175.2 1914.78     185 1915.08   194.7 1915.74
   214.2  1917.8   223.9 1918.94   233.6  1920.2   253.1 1922.92   262.8 1924.41
   271.41925.832   281.8 1927.67     291 1929.45   300.2  1931.5  307.371933.399
   318.5 1936.58   346.1 1944.95
#Mann= 5 ,-1 , 0
       0     .12       0   114.1    .045       0  128.05     .12       0
   271.4    .016       0  307.37     .12       0
Bank Sta=114.1,128.05
XS Rating Curve= 0 ,0
Exp/Cntr=0.3,0.1

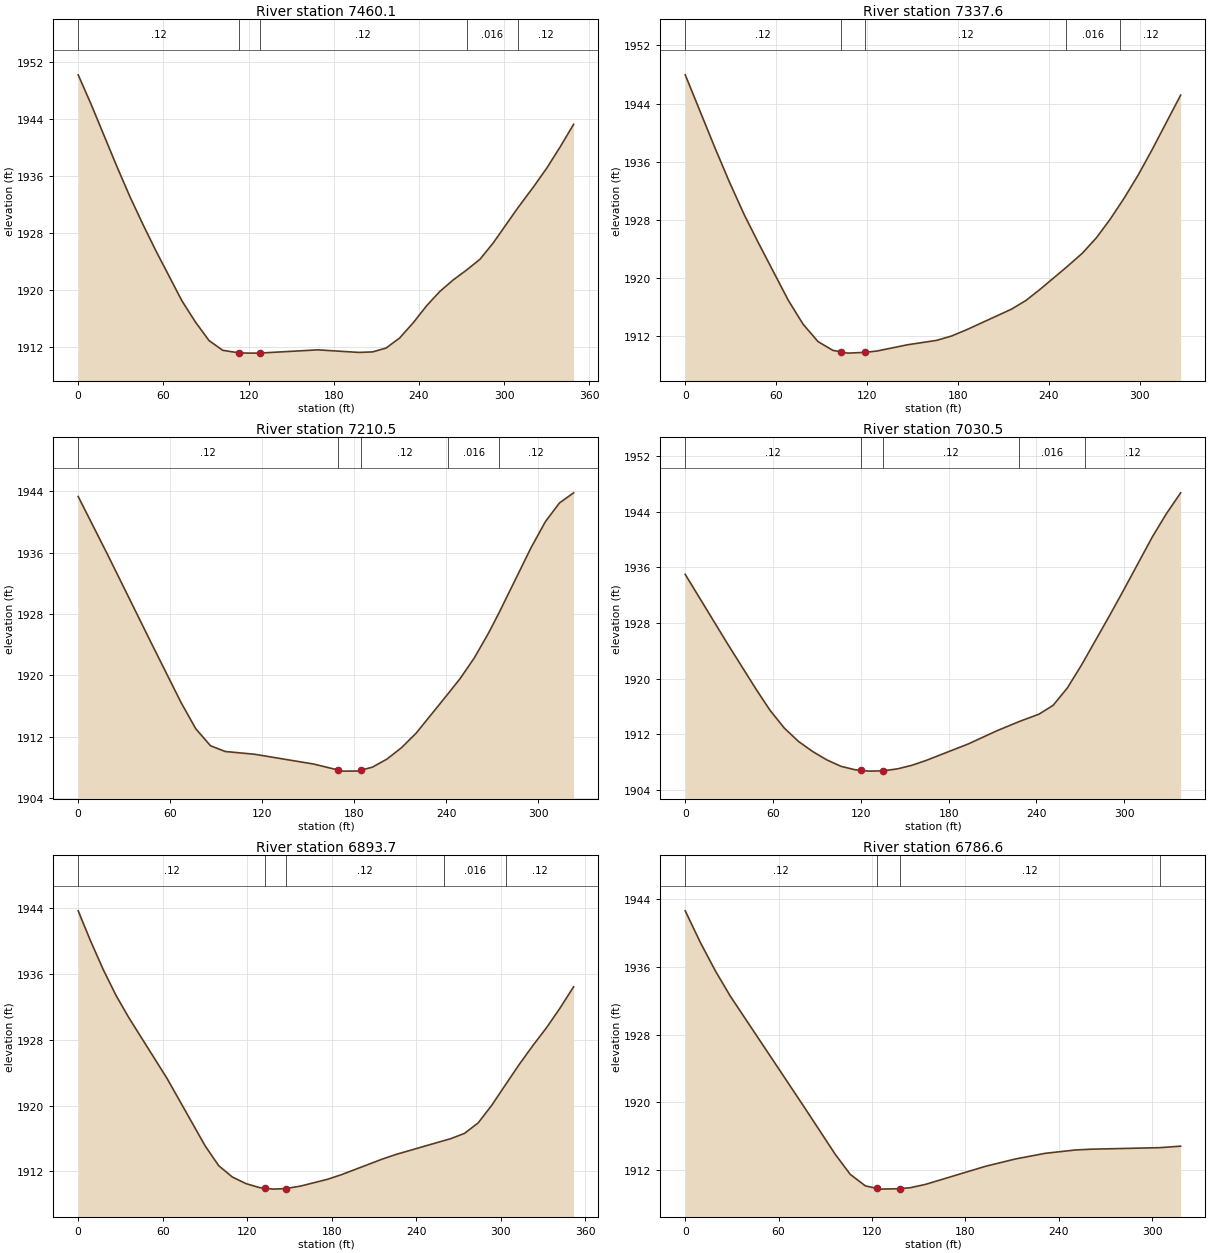
Type RM Length L Ch R = 1 ,7460.1  ,117.2,122.6,129.1
XS GIS Cut Line= 4
     1816178.627      181328.764     1816249.808      181345.257
     1816407.794      181305.327     1816519.493      181322.228
#Sta/Elev= 30
       0 1950.21     9.1 1946.08    27.4 1937.29    36.5 1933.11    45.7  1929.2
    54.8 1925.52    73.1 1918.52    82.6 1915.55    92.2 1912.95   101.8 1911.59
  113.181911.225     121 1911.19  127.891911.198   168.9 1911.65   197.7 1911.29
   207.3 1911.36   216.8 1911.89   226.4  1913.3     236 1915.44   245.4 1917.82
   254.8 1919.84   264.3 1921.47  273.731922.855   283.1 1924.36   292.5 1926.67
   309.81931.577   320.8 1934.51   330.2 1937.16   339.6 1940.12     349 1943.27
#Mann= 5 ,-1 , 0
       0     .12       0  113.18    .045       0  127.89     .12       0
  273.73    .016       0   309.8     .12       0
Bank Sta=113.18,127.89
XS Rating Curve= 0 ,0
Exp/Cntr=0.3,0.1

Type RM Length L Ch R = 1 ,7337.6  ,120.3,127,131.9
XS GIS Cut Line= 4
     1816163.002      181437.271     1816228.928      181453.996
     1816385.644       181449.12      1816486.07      181467.499
#Sta/Elev= 29
       0 1947.96    19.4 1938.02    29.2 1933.19    38.9 1928.73    48.6 1924.71
      68 1916.94    77.8 1913.64    87.6 1911.26    97.4 1910.05  102.941909.835
   107.2 1909.67  118.94 1909.78   126.8 1909.97   146.4 1910.81     166 1911.43
   175.8 1912.03   185.6 1912.88     215 1915.69   224.8 1916.91   234.1 1918.44
  251.331921.456   261.9 1923.39   271.2 1925.51   280.5 1928.12  287.061930.187
   289.8 1931.05   299.1 1934.25   308.3 1937.75   326.9 1945.17
#Mann= 5 ,-1 , 0
       0     .12       0  102.94    .045       0  118.94     .12       0
  251.33    .016       0  287.06     .12       0
Bank Sta=102.94,118.94
XS Rating Curve= 0 ,0
Exp/Cntr=0.3,0.1

Type RM Length L Ch R = 1 ,7210.5  ,178.1,180,183.1
XS GIS Cut Line= 3
     1816149.113      181520.604     1816391.301      181579.632
     1816465.098      181582.316
#Sta/Elev= 26
       0  1943.3    19.2 1935.72    47.9 1924.11    67.1 1916.44    76.7 1913.02
    86.3 1910.81    95.9 1910.06     115  1909.7   153.4 1908.43   169.7 1907.64
   172.6  1907.5   182.2 1907.51   184.7 1907.64   191.8 1908.01   201.3 1909.06
   210.9 1910.56   220.5 1912.47  241.461917.644   249.3 1919.62   258.5 1922.31
   267.7 1925.52  274.431928.125   295.4 1936.64   304.7 1940.02   313.9 1942.46
   323.1 1943.78
#Mann= 5 ,-1 , 0
       0     .12       0   169.7    .045       0   184.7     .12       0
  241.46    .016       0  274.43     .12       0
Bank Sta=169.7,184.7
XS Rating Curve= 0 ,0
Exp/Cntr=0.3,0.1

Type RM Length L Ch R = 1 ,7030.5  ,135.3,136.8,137.9
XS GIS Cut Line= 2
     1816103.106      181662.097     1816418.239      181785.595
#Sta/Elev= 29
       0    1935      29 1924.99    48.4 1918.49      58 1915.44    67.7  1912.9
    77.4 1910.98      87 1909.54    96.7 1908.33   106.4  1907.4     116 1906.91
   120.3 1906.82   125.7 1906.71   135.3 1906.75   145.1 1907.04   154.7 1907.54
   164.4 1908.23   193.4 1910.62   212.8  1912.5  228.151913.836   241.8 1914.91
   251.4 1916.18   261.1 1918.67   270.8 1921.98  273.45 1922.96   290.1 1929.14
   299.8 1932.84   319.1 1940.37   328.8 1943.74   338.5 1946.73
#Mann= 5 ,-1 , 0
       0     .12       0   120.3    .045       0   135.3     .12       0
  228.15    .016       0  273.45     .12       0
Bank Sta=120.3,135.3
XS Rating Curve= 0 ,0
Exp/Cntr=0.3,0.1

Type RM Length L Ch R = 1 ,6893.7  ,86.9,107,126.6
XS GIS Cut Line= 3
     1816031.477      181740.787      1816101.79       181797.21
     1816339.637      181906.585
#Sta/Elev= 30
       0 1943.65       9 1939.91      18 1936.44      27 1933.34    36.1 1930.64
    63.1  1923.3    90.2  1915.1    99.8  1912.7   109.5 1911.32   119.2 1910.52
   128.9 1910.03   132.4 1909.97   138.6 1909.85   147.4 1909.92     158 1910.22
   177.4 1911.06   187.1 1911.61   216.2 1913.51   225.9 1914.07  260.121915.758
   264.7 1915.98   274.4 1916.62   284.1 1917.89   293.8 1920.04  303.54 1922.53
   313.2 1924.97   322.9 1927.27   332.6 1929.44   342.2 1931.82   351.9 1934.42
#Mann= 5 ,-1 , 0
       0     .12       0   132.4    .045       0   147.4     .12       0
  260.12    .016       0  303.54     .12       0
Bank Sta=132.4,147.4
XS Rating Curve= 0 ,0
Exp/Cntr=0.3,0.1

Type RM Length L Ch R = 1 ,6786.6  ,320.4,320.1,317.4
XS GIS Cut Line= 2
     1816026.269      181747.731     1816109.602      182055.023
#Sta/Elev= 20
       0 1942.64     9.6 1938.94    19.3 1935.56    28.9 1932.57    77.2 1919.23
    96.5 1913.82   106.1 1911.47   115.8 1910.11  123.161909.817   125.4 1909.73
  137.91 1909.78   144.7  1909.9   154.4 1910.29     193 1912.43   212.3  1913.3
   231.6 1913.97   250.8 1914.36   260.5 1914.45  304.931914.633   318.4 1914.81
#Mann= 4 ,-1 , 0
       0     .12       0  123.16    .045       0  137.91     .12       0
  304.93    .016       0
Bank Sta=123.16,137.91
XS Rating Curve= 0 ,0
Exp/Cntr=0.3,0.1