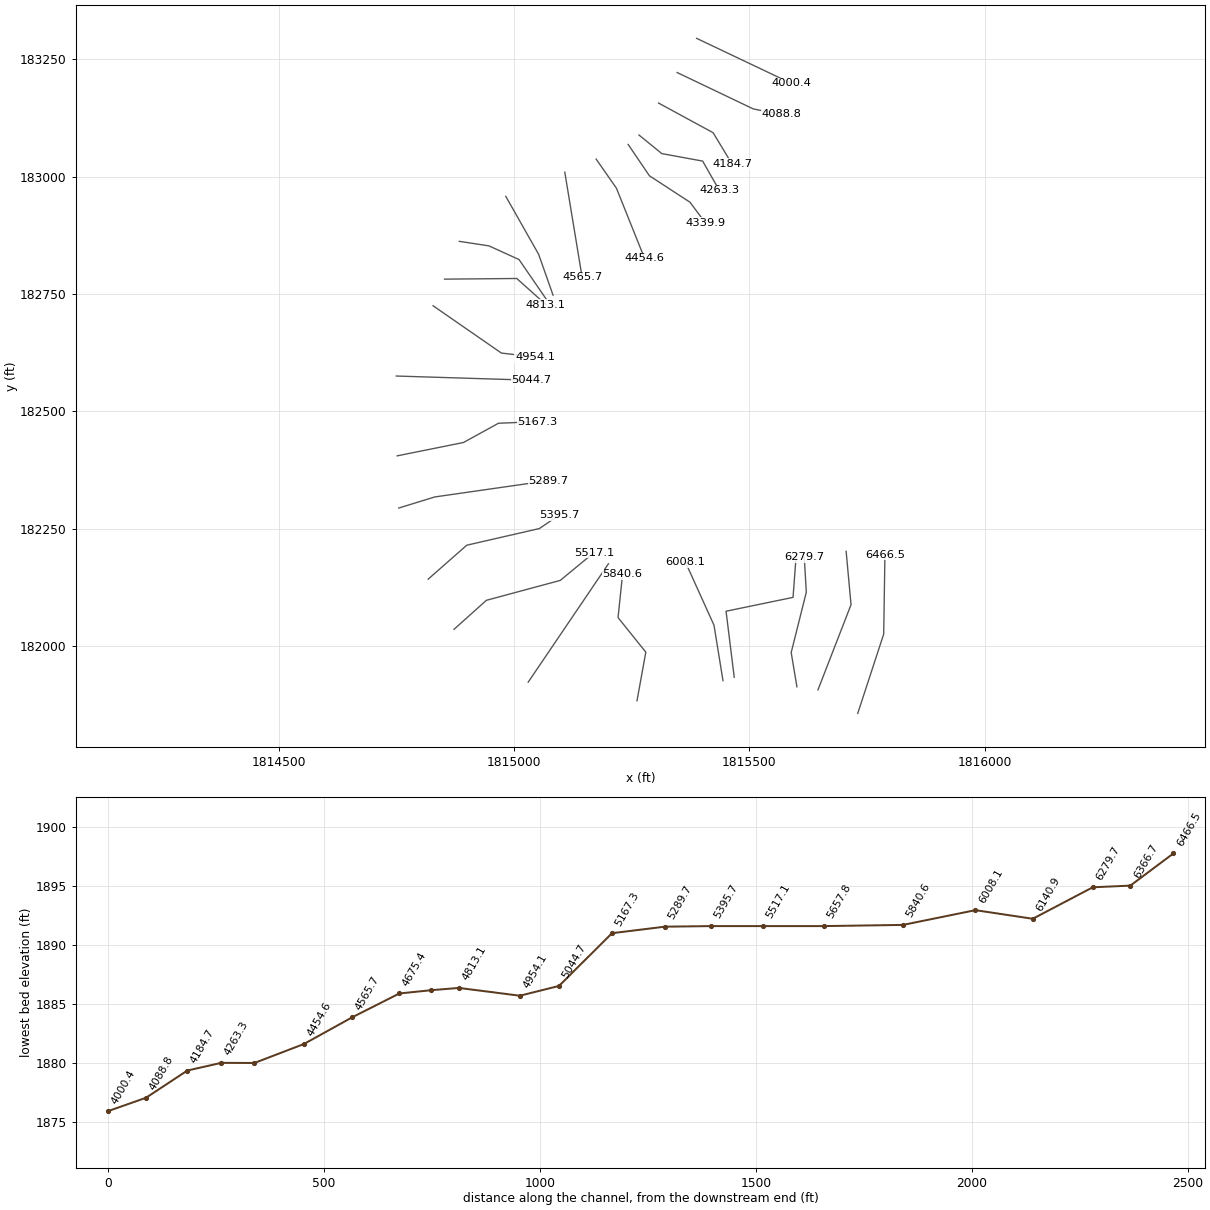
HEC-RAS study HANGINGRN.prj: HANGINGRN

--- HANGINGRN.g01 (geometry) --- (continued)

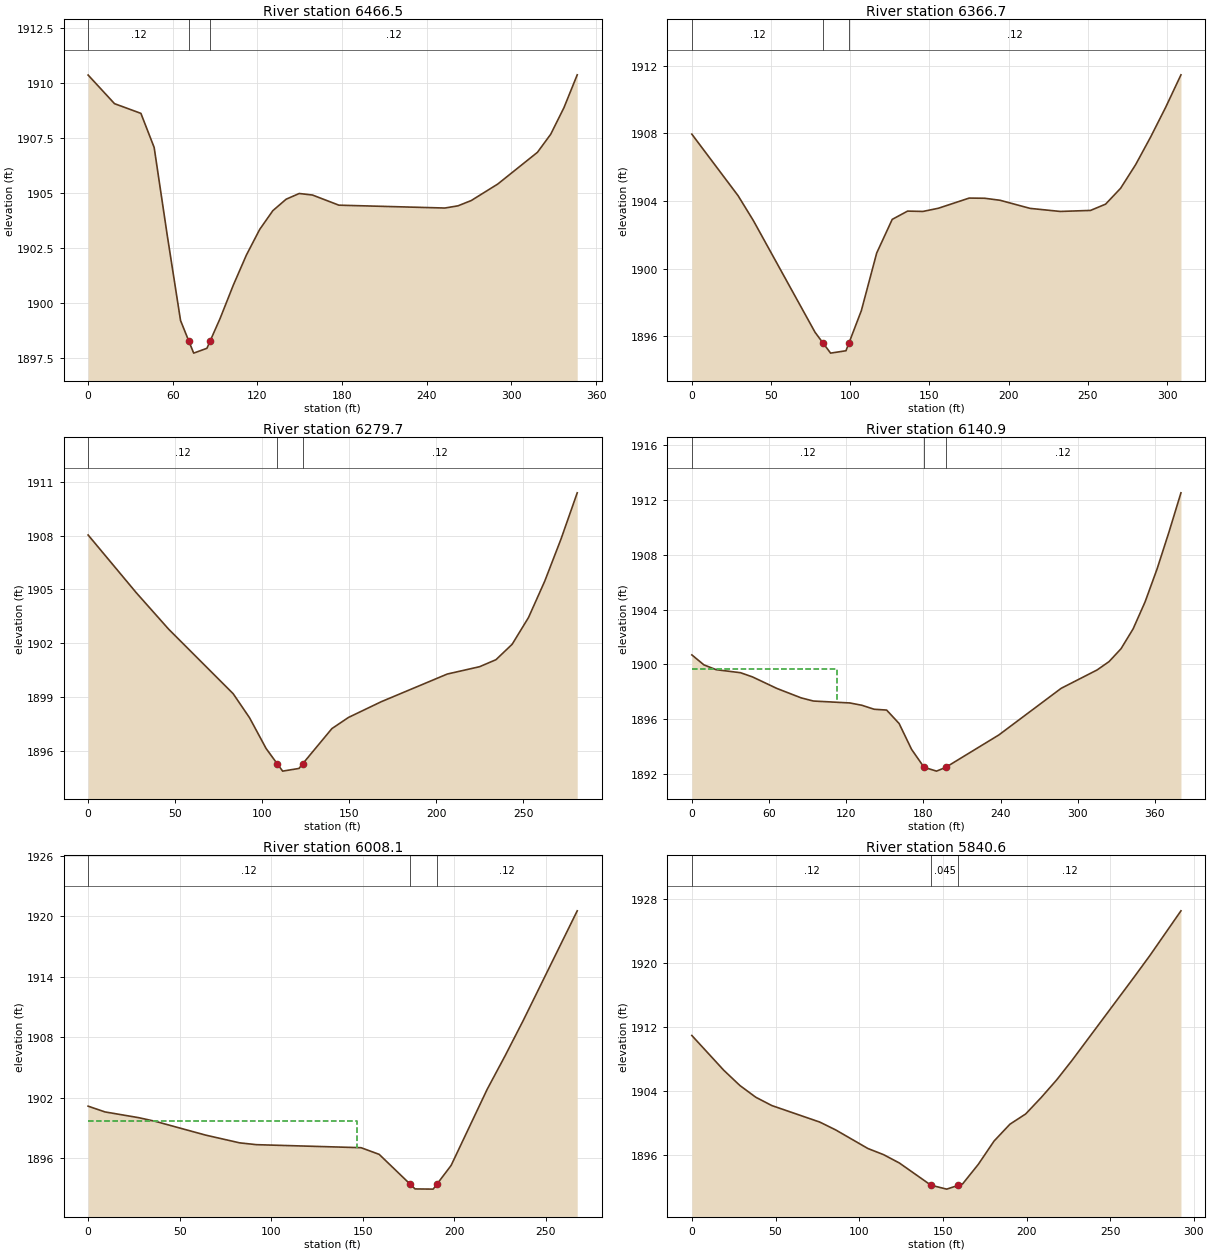
Type RM Length L Ch R = 1 ,6466.5  ,101.3,99.7,98.1
XS GIS Cut Line= 3
     1815730.236       181856.88     1815785.398      182025.813
     1815787.982      182194.647
#Sta/Elev= 27
       0 1910.37    18.7 1909.07    37.4 1908.63    46.8 1907.08    56.1 1903.08
    65.5 1899.22   71.291898.298    74.8 1897.74    84.2 1897.96   86.411898.284
    93.5 1899.31   102.9 1900.83   112.2  1902.2   121.6 1903.36   130.9 1904.21
   140.3 1904.73   149.6 1904.99     159 1904.92   177.7 1904.46   252.8 1904.33
   262.1 1904.43   271.5 1904.67   290.3 1905.42   318.4 1906.86   327.8 1907.68
   337.2 1908.89   346.6 1910.38
#Mann= 3 ,-1 , 0
       0     .12       0   71.29    .045       0   86.41     .12       0
Bank Sta=71.29,86.41
XS Rating Curve= 0 ,0
Exp/Cntr=0.3,0.1

Type RM Length L Ch R = 1 ,6366.7  ,84,87,89.7
XS GIS Cut Line= 3
     1815645.641      181906.889     1815715.954      182088.313
     1815705.537      182202.028
#Sta/Elev= 26
       0 1907.96    29.2 1904.32    38.9 1902.84    77.8 1896.24    82.91895.597
    87.6 1895.01    97.3 1895.15    99.11895.587     107 1897.52   116.7 1900.93
   126.5 1902.92   136.2 1903.41   145.9 1903.39   155.7 1903.58   175.1 1904.18
   184.8 1904.17   194.6 1904.05   213.6 1903.57   232.6 1903.39   251.7 1903.45
   261.2 1903.82   270.7 1904.76   280.2 1906.16   289.7  1907.8   299.2 1909.56
   308.8 1911.47
#Mann= 3 ,-1 , 0
       0     .12       0    82.9    .045       0    99.1     .12       0
Bank Sta=82.9,99.1
XS Rating Curve= 0 ,0
Exp/Cntr=0.3,0.1

Type RM Length L Ch R = 1 ,6279.7  ,164.1,138.8,111
XS GIS Cut Line= 4
     1815600.922       181913.53     1815588.769      181986.446
     1815620.887      182114.919     1815616.547      182189.571
#Sta/Elev= 21
       0 1908.03    27.7 1904.81    46.2 1902.79    83.4 1899.18    92.8 1897.84
   102.3 1896.13  108.671895.282   111.8 1894.87   121.2 1895.02  123.351895.283
   140.1 1897.24   149.6 1897.86   168.5 1898.74   206.4 1900.28     225 1900.69
   234.4 1901.08   243.7 1901.94   253.1 1903.43   262.4 1905.45   271.8 1907.81
   281.1 1910.38
#Mann= 3 ,-1 , 0
       0     .12       0  108.67    .045       0  123.35     .12       0
Bank Sta=108.67,123.35
XS Rating Curve= 0 ,0
Exp/Cntr=0.3,0.1

Type RM Length L Ch R = 1 ,6140.9  ,91.9,132.8,173.8
XS GIS Cut Line= 4
      1815467.69      181933.799     1815450.329      182074.424
      1815592.69      182103.938     1815599.634       182196.82
#Sta/Elev= 27
       0 1900.69     9.4 1899.96    18.9 1899.61    37.8 1899.39    47.2 1899.08
    66.1 1898.24      85 1897.55    94.5 1897.32   122.8 1897.18   132.2 1897.01
   141.7 1896.72   151.4 1896.66   161.1 1895.68   170.8 1893.79   180.5 1892.48
   190.2  1892.2  197.261892.471   238.6 1894.84   287.1 1898.25     315 1899.59
   324.3  1900.2   333.6 1901.14     343 1902.59   352.3 1904.56   361.6 1906.96
   370.9 1909.67   380.2 1912.53
#Mann= 3 ,-1 , 0
       0     .12       0   180.5    .045       0  197.26     .12       0
#XS Ineff= 2 , 0
          113.11 1899.67
Permanent Ineff=
       F       F
Bank Sta=180.5,197.26
XS Rating Curve= 0 ,0
Exp/Cntr=0.3,0.1

Type RM Length L Ch R = 1 ,6008.1  ,161.8,167.6,173.1
XS GIS Cut Line= 3
     1815443.804      181926.551     1815424.707      182044.606
     1815363.943      182179.155
#Sta/Elev= 18
       0 1901.16     9.2 1900.59    27.6 1900.02    36.8 1899.65    64.4 1898.28
    82.8 1897.52      92 1897.34   149.1 1897.04     159 1896.38  175.981893.414
   178.6 1892.95   188.5 1892.93  190.591893.428   198.3 1895.28     218 1902.83
   227.8 1906.16   237.7 1909.66   267.2 1920.54
#Mann= 3 ,-1 , 0
       0     .12       0  175.98    .045       0  190.59     .12       0
#XS Ineff= 2 , 0
          146.75 1899.64
Permanent Ineff=
       F       F
Bank Sta=175.98,190.59
XS Rating Curve= 0 ,0
Exp/Cntr=0.3,0.1

Type RM Length L Ch R = 1 ,5840.6  ,211.6,182.8,153.6
XS GIS Cut Line= 4
     1815261.049      181883.799     1815279.799      181987.271
     1815220.771      182060.882     1815230.394      182153.142
#Sta/Elev= 24
       0 1910.89    19.1 1906.54    28.7 1904.64    38.2 1903.17    47.8 1902.13
    76.5 1900.06      86 1899.08   105.2 1896.76   114.6 1895.99     124 1894.95
   142.9 1892.17   152.3 1891.68  159.061892.141   161.8 1892.33   171.2 1894.78
   180.6 1897.69   190.1  1899.8   199.5 1901.08   208.8 1903.14   218.1 1905.36
   227.3 1907.81   264.4 1918.22   273.7 1920.88   292.3 1926.48
#Mann= 3 ,-1 , 0
       0     .12       0   142.9    .045       0  159.06     .12       0
Bank Sta=142.9,159.06
XS Rating Curve= 0 ,0
Exp/Cntr=0.3,0.1

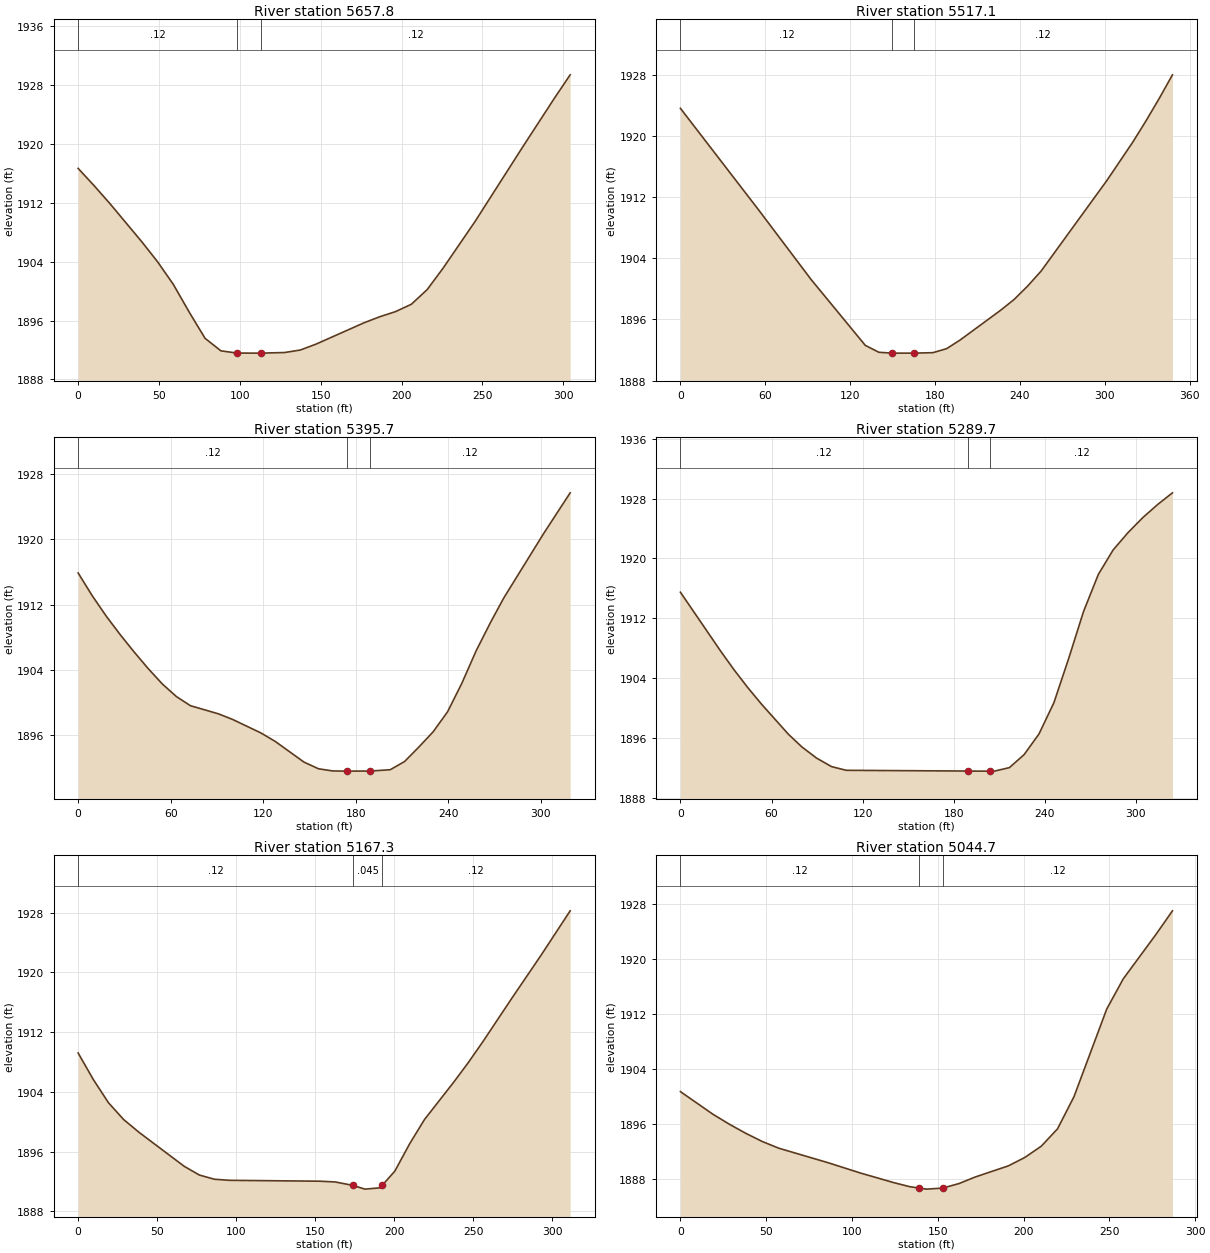
Type RM Length L Ch R = 1 ,5657.8  ,156.7,140.7,124.4
XS GIS Cut Line= 2
     1815029.799      181923.382     1815200.252      182175.414
#Sta/Elev= 25
       0 1916.68     9.8 1914.35    19.6 1911.91    39.3 1906.73    49.1    1904
    58.9 1900.91    68.7 1897.15    78.5 1893.59    88.3 1891.89    98.2 1891.59
     108 1891.58  112.94 1891.58   127.6 1891.66   137.4    1892   147.2 1892.81
   176.7 1895.69   186.5 1896.52   196.3 1897.22   206.1 1898.22   215.9 1900.22
   225.7 1903.12   245.4 1909.44   274.8 1919.54   294.4 1926.16   304.3 1929.39
#Mann= 3 ,-1 , 0
       0     .12       0    98.2    .045       0  112.94     .12       0
Bank Sta=98.2,112.94
XS Rating Curve= 0 ,0
Exp/Cntr=0.3,0.1

Type RM Length L Ch R = 1 ,5517.1  ,122.3,121.4,120.6
XS GIS Cut Line= 4
      1814872.16      182035.882      1814940.91      182097.688
     1815097.855      182140.049     1815169.382      182199.077
#Sta/Elev= 19
       0 1923.59    55.5 1910.25    92.4  1901.2   130.7 1892.59   140.3 1891.69
   149.8 1891.58  165.13 1891.58   178.5 1891.64   188.1 1892.16   197.6 1893.28
   226.3 1897.18   235.9  1898.6   245.4 1900.34     255 1902.32   301.4 1914.14
   319.9 1919.21   329.2 1921.98   338.5  1924.9   347.8 1927.97
#Mann= 3 ,-1 , 0
       0     .12       0   149.8    .045       0  165.13     .12       0
Bank Sta=149.8,165.13
XS Rating Curve= 0 ,0
Exp/Cntr=0.3,0.1

Type RM Length L Ch R = 1 ,5395.7  ,107.9,106,104.1
XS GIS Cut Line= 4
     1814817.299      182142.827     1814899.244      182215.049
      1815053.41      182250.465     1815096.071      182279.453
#Sta/Elev= 29
       0 1915.87     9.1 1913.09    18.2 1910.58    27.3  1908.3    36.4 1906.16
    45.5 1904.13    54.6 1902.26    63.7 1900.72    72.8  1899.6      91  1898.6
   100.1 1897.92   118.5 1896.26   127.8 1895.22   146.4 1892.69   155.8 1891.87
   165.1  1891.6   174.3 1891.58   189.3 1891.59   202.3 1891.75   211.6 1892.75
   220.9 1894.53   230.2 1896.41   239.5 1898.85   248.8 1902.36   258.1 1906.35
   267.4 1909.82     276 1912.82   301.8  1920.7     319 1925.69
#Mann= 3 ,-1 , 0
       0     .12       0   174.3    .045       0   189.3     .12       0
Bank Sta=174.3,189.3
XS Rating Curve= 0 ,0
Exp/Cntr=0.3,0.1

Type RM Length L Ch R = 1 ,5289.7  ,114.1,122.3,130.6
XS GIS Cut Line= 3
     1814754.799      182294.215     1814831.188      182317.827
     1815072.855      182352.549
#Sta/Elev= 26
       0 1915.47    26.6 1907.56    35.5 1905.04    44.4  1902.7    53.3 1900.52
    71.1 1896.47      80 1894.77    89.7 1893.27    99.5 1892.14   109.2 1891.64
   189.2 1891.54   197.2 1891.53   204.2 1891.53   206.9 1891.53   216.7    1892
   226.4 1893.74   236.2 1896.51     246 1900.68   255.7 1906.57   265.5 1912.87
   275.3 1917.86     285 1921.12   294.8 1923.44   304.6 1925.46   314.3  1927.2
   324.1 1928.77
#Mann= 3 ,-1 , 0
       0     .12       0   189.2    .045       0   204.2     .12       0
Bank Sta=189.2,204.2
XS Rating Curve= 0 ,0
Exp/Cntr=0.3,0.1

Type RM Length L Ch R = 1 ,5167.3  ,134.7,122.7,110.3
XS GIS Cut Line= 4
     1814751.327      182405.327     1814892.299      182433.799
     1814966.605      182474.771     1815049.244      182478.243
#Sta/Elev= 24
       0 1909.21     9.6 1905.66    19.2 1902.55    28.8  1900.3    38.4 1898.61
    67.1 1894.04    76.7 1892.87    86.3  1892.3    95.9 1892.16   153.2 1892.04
   162.7 1891.94  173.961891.478   181.5 1890.98     191 1891.15  192.441891.493
   200.4 1893.38   209.8 1897.05   219.2  1900.3   237.9 1905.36     247 1907.95
   256.2 1910.74   274.6 1916.58     293 1922.31   311.4 1928.25
#Mann= 3 ,-1 , 0
       0     .12       0  173.96    .045       0  192.44     .12       0
Bank Sta=173.96,192.44
XS Rating Curve= 0 ,0
Exp/Cntr=0.3,0.1

Type RM Length L Ch R = 1 ,5044.7  ,103.4,90.6,77.2
XS GIS Cut Line= 2
     1814749.432      182575.352     1815036.049      182566.438
#Sta/Elev= 24
       0  1900.7    19.1 1897.38    28.7 1895.93    38.2 1894.62    47.8 1893.43
    57.4 1892.46      86 1890.36   105.1 1888.84   124.3 1887.46   133.8 1886.86
   139.3 1886.66   143.4 1886.51   152.9 1886.66   162.5 1887.33     172 1888.29
   191.2  1889.9   200.7 1891.11   210.3 1892.75   219.8 1895.28   229.4 1899.96
   248.5 1912.72   258.1  1917.1   277.2 1923.58   286.8 1927.01
#Mann= 3 ,-1 , 0
       0     .12       0   139.3    .045       0   152.9     .12       0
Bank Sta=139.3,152.9
XS Rating Curve= 0 ,0
Exp/Cntr=0.3,0.1

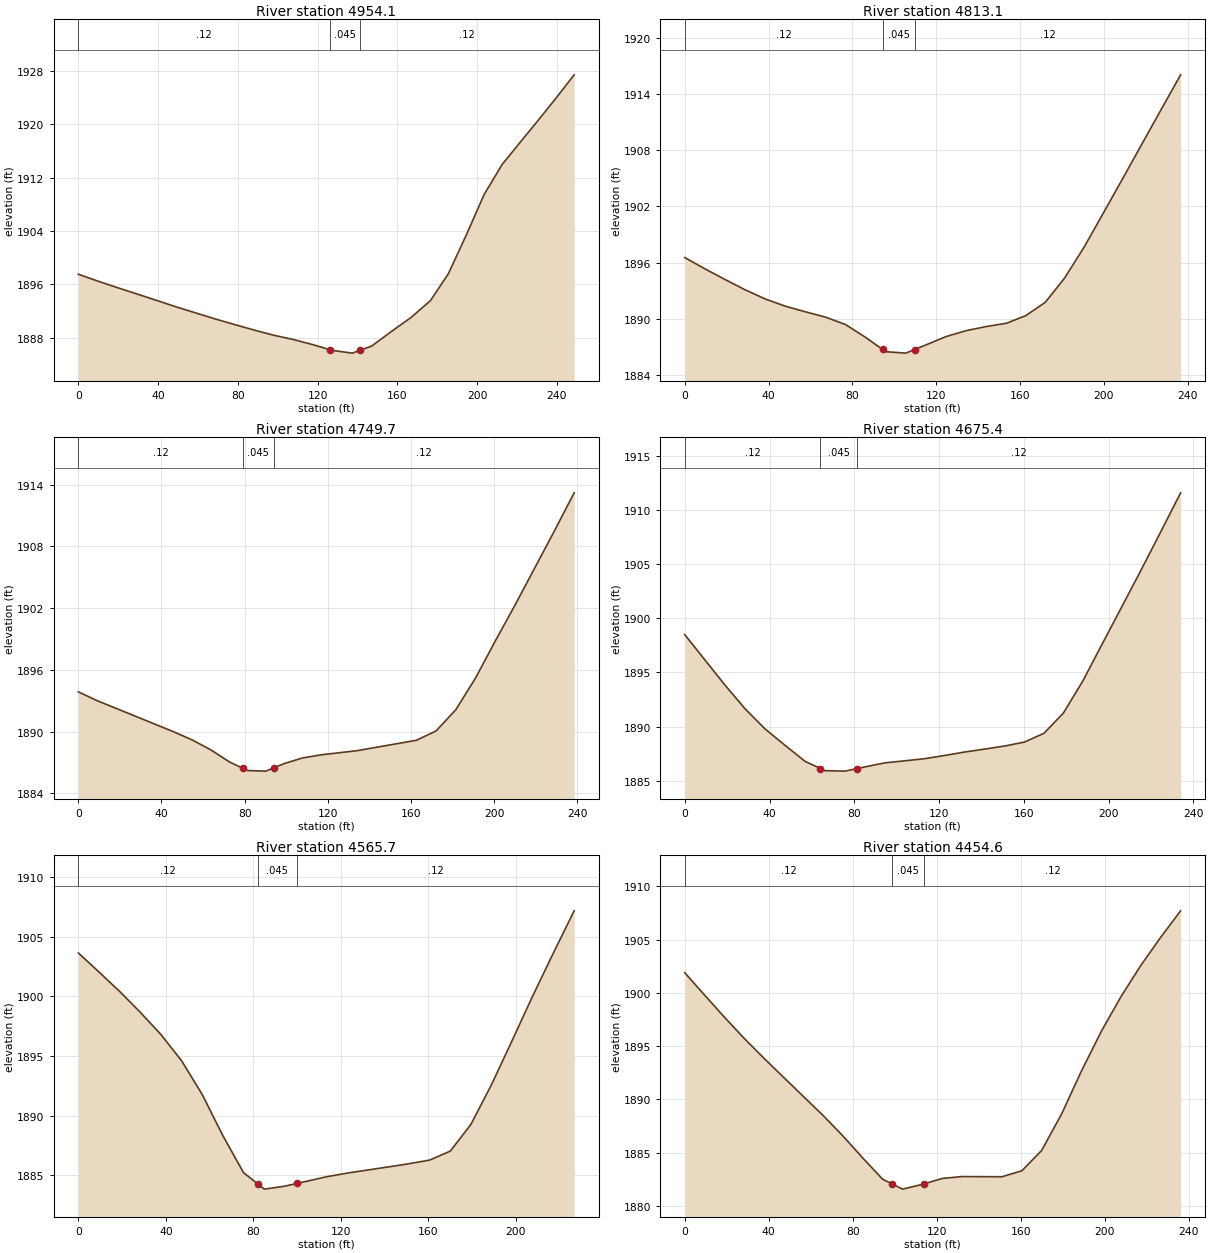
Type RM Length L Ch R = 1 ,4954.1  ,126.1,141,155.5
XS GIS Cut Line= 3
     1814827.716      182724.945     1814972.855       182624.25
     1815044.382      182615.917
#Sta/Elev= 30
       0 1897.52     9.8 1896.49    19.6 1895.51    29.4 1894.56    39.3 1893.59
    49.1 1892.62    58.9 1891.71    68.7 1890.81    78.5 1889.96    88.3 1889.13
    98.1 1888.36     108 1887.71   117.8 1886.94  126.431886.176   127.4 1886.09
   137.4 1885.68  141.391886.119   142.4 1886.23   147.2 1886.75     157 1888.92
   166.8 1891.01   176.6 1893.55   185.6 1897.59   194.6 1903.41   203.6 1909.52
   212.6    1914   221.7 1917.35   230.7 1920.64   239.7 1923.99   248.7 1927.45
#Mann= 3 ,-1 , 0
       0     .12       0  126.43    .045       0  141.39     .12       0
Bank Sta=126.43,141.39
XS Rating Curve= 0 ,0
Exp/Cntr=0.3,0.1

Type RM Length L Ch R = 1 ,4813.1  ,73.6,63.5,53.6
XS GIS Cut Line= 3
     1814852.021      182781.715     1815005.494      182783.104
     1815067.299      182727.549
#Sta/Elev= 30
       0 1896.54     9.6 1895.34    19.2  1894.2    28.8  1893.1    38.4 1892.12
      48 1891.35    57.6 1890.75    67.2 1890.18    76.7 1889.39    86.3 1888.02
      92 1887.11   94.39 1886.73    95.9 1886.49   105.5 1886.34     107 1886.48
  109.661886.723   115.1 1887.22   124.7 1888.11   134.3 1888.74   143.9 1889.18
   153.5 1889.53   162.7 1890.34     172 1891.76   181.2 1894.34   190.4  1897.6
   199.6 1901.24   208.9 1904.95   218.1 1908.65   227.4 1912.38   236.6 1916.05
#Mann= 3 ,-1 , 0
       0     .12       0   94.39    .045       0  109.66     .12       0
Bank Sta=94.39,109.66
XS Rating Curve= 0 ,0
Exp/Cntr=0.3,0.1

Type RM Length L Ch R = 1 ,4749.7  ,88.3,74.3,59.7
XS GIS Cut Line= 4
     1814883.311      182862.221     1814946.466      182852.549
     1815010.355      182823.382     1815069.382      182737.271
#Sta/Elev= 22
       0 1893.86     9.1    1893    45.6    1890    54.8 1889.18    63.9  1888.2
    72.7 1887.04   79.161886.427    81.4 1886.21    90.2 1886.15   93.991886.469
      99 1886.88   107.8 1887.43   116.6 1887.73   134.1 1888.14   162.6 1889.15
   172.1 1890.06   181.6 1892.13   191.1 1895.22   200.6 1898.82     210 1902.28
     229 1909.51   238.5 1913.22
#Mann= 3 ,-1 , 0
       0     .12       0   79.16    .045       0   93.99     .12       0
Bank Sta=79.16,93.99
XS Rating Curve= 0 ,0
Exp/Cntr=0.3,0.1

Type RM Length L Ch R = 1 ,4675.4  ,117.5,109.7,101.7
XS GIS Cut Line= 3
     1814982.164      182958.037     1815052.021      182834.493
     1815082.577      182747.688
#Sta/Elev= 30
       0  1898.5     9.5 1896.16    18.9 1893.85    28.4 1891.65    37.8 1889.79
    47.3 1888.26    56.8 1886.77    62.3 1886.27   64.041886.109    66.2 1885.91
    75.7 1885.87    77.3 1885.94   81.36 1886.11    85.2 1886.27    94.6 1886.64
   104.1 1886.83   113.5 1887.03     123 1887.33   132.5 1887.65   141.9 1887.92
   151.1  1888.2   160.3 1888.56   169.5 1889.37   178.7 1891.25   187.9 1894.23
   197.1 1897.68   206.4 1901.14   215.6 1904.58   224.8 1908.09     234 1911.63
#Mann= 3 ,-1 , 0
       0     .12       0   64.04    .045       0   81.36     .12       0
Bank Sta=64.04,81.36
XS Rating Curve= 0 ,0
Exp/Cntr=0.3,0.1

Type RM Length L Ch R = 1 ,4565.7  ,105.5,111,115.8
XS GIS Cut Line= 2
     1815107.577      183009.493     1815144.382      182785.882
#Sta/Elev= 29
       0 1903.64     9.4 1902.05    18.9 1900.41    28.3 1898.67    37.8 1896.79
    47.2  1894.6    56.6 1891.78    66.1 1888.31    75.5 1885.22    78.7 1884.76
   81.99 1884.28      85 1883.84    93.7 1884.07    94.4 1884.09   99.941884.317
   103.9 1884.48   113.3 1884.87   122.8 1885.18   132.2 1885.44   141.6  1885.7
   151.1 1885.97   160.5 1886.27     170 1887.03   179.4 1889.26   188.8 1892.59
   198.3 1896.31   207.7 1900.05   217.2 1903.67   226.6 1907.17
#Mann= 3 ,-1 , 0
       0     .12       0   81.99    .045       0   99.94     .12       0
Bank Sta=81.99,99.94
XS Rating Curve= 0 ,0
Exp/Cntr=0.3,0.1

Type RM Length L Ch R = 1 ,4454.6  ,98.6,114.7,128.6
XS GIS Cut Line= 3
     1815174.244      183037.271     1815217.299      182975.465
     1815277.021       182826.16
#Sta/Elev= 29
       0 1901.89     9.4  1899.8    18.8 1897.74    28.2 1895.75    37.7 1893.87
    47.1 1892.07    56.5 1890.28    65.9 1888.49    75.3 1886.58    84.8  1884.5
    94.2 1882.52      98 1882.15   98.731882.078   103.7 1881.59     113 1882.03
  114.061882.092   122.6 1882.59   132.1 1882.77   141.5 1882.76     151 1882.75
   160.5 1883.31   169.9 1885.21   179.4 1888.63   188.8 1892.64   198.3 1896.38
   207.8 1899.68   217.2 1902.59   226.7 1905.24   236.1  1907.7
#Mann= 3 ,-1 , 0
       0     .12       0   98.73    .045       0  114.06     .12       0
Bank Sta=98.73,114.06
XS Rating Curve= 0 ,0
Exp/Cntr=0.3,0.1

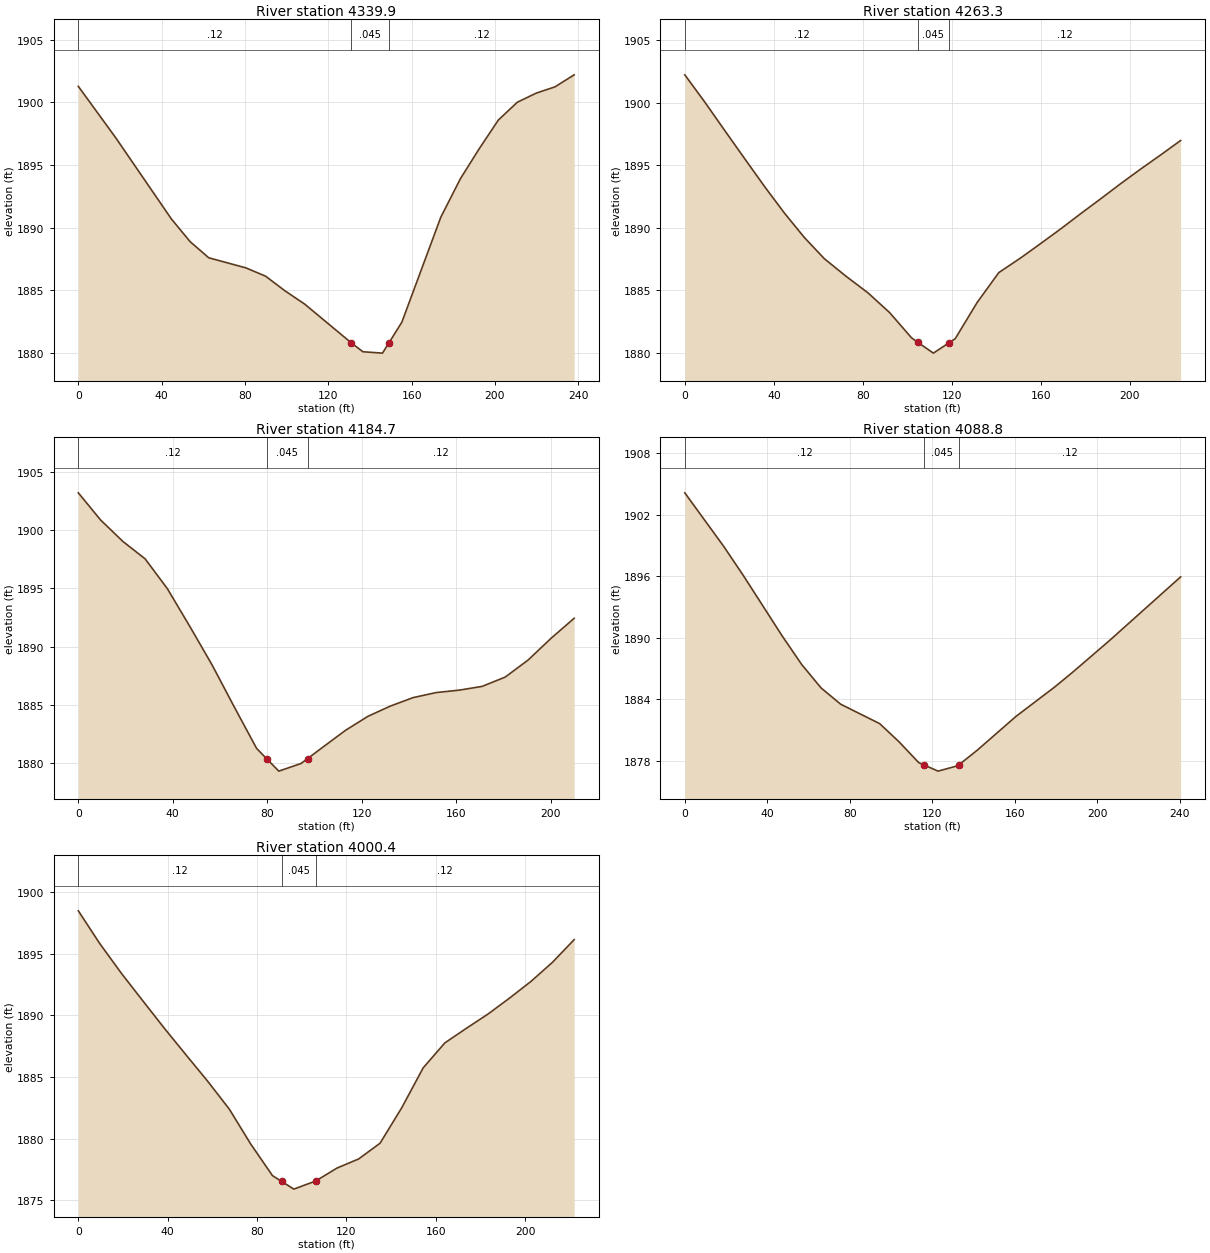
Type RM Length L Ch R = 1 ,4339.9  ,68.8,76.6,85.7
XS GIS Cut Line= 4
     1815242.299      183068.521     1815287.438      183001.854
     1815373.549      182945.604     1815406.188      182901.854
#Sta/Elev= 22
       0 1901.27    17.9 1897.18    44.7 1890.68    53.7 1888.87    62.6 1887.59
    80.5 1886.78    89.9 1886.12    99.2 1884.95   108.6  1883.9  131.021880.801
   136.6 1880.09     146 1879.98  149.041880.784   155.3 1882.45     174 1890.83
   183.4  1893.9   192.5 1896.31   201.6 1898.58   210.7    1900   219.8 1900.73
   228.8 1901.23     238 1902.19
#Mann= 3 ,-1 , 0
       0     .12       0  131.02    .045       0  149.04     .12       0
Bank Sta=131.02,149.04
XS Rating Curve= 0 ,0
Exp/Cntr=0.3,0.1

Type RM Length L Ch R = 1 ,4263.3  ,85.7,78.5,71.3
XS GIS Cut Line= 4
     1815265.216       183088.66     1815313.827      183049.077
     1815400.632      183033.104     1815436.049      182970.604
#Sta/Elev= 29
       0 1902.24       9 1900.06    17.9  1897.8    26.9 1895.54    35.8 1893.32
    44.8 1891.18    53.7 1889.24    62.7 1887.54    72.5 1886.13    82.3 1884.81
    92.1 1883.22   101.9 1881.21  104.841880.841   105.8 1880.72   111.7 1879.99
   118.61880.801   120.8 1881.06   121.5 1881.14   131.3 1884.02   141.1 1886.43
     151 1887.61   159.9 1888.75   168.9 1889.92   177.9 1891.14   186.9 1892.33
   195.8 1893.53   204.8  1894.7   213.8 1895.83   222.8 1896.99
#Mann= 3 ,-1 , 0
       0     .12       0  104.84    .045       0   118.6     .12       0
Bank Sta=104.84,118.6
XS Rating Curve= 0 ,0
Exp/Cntr=0.3,0.1

Type RM Length L Ch R = 1 ,4184.7  ,94.3,95.9,97.4
XS GIS Cut Line= 3
     1815306.882      183156.715     1815422.855      183093.521
     1815463.132      183026.854
#Sta/Elev= 27
       0 1903.19     9.4 1900.87    18.9 1899.02    28.3 1897.53    37.7 1894.98
    47.2 1891.75    56.6 1888.46      66 1884.86    75.5 1881.29    77.7 1880.83
   79.831880.389    84.9 1879.34    92.7 1879.88    94.3 1879.99   97.081880.411
   103.8 1881.43   113.2 1882.84   122.6 1884.03   132.1 1884.91   141.8 1885.64
   151.5 1886.07   161.3 1886.28     171  1886.6   180.8  1887.4   190.5 1888.86
   200.2 1890.72     210 1892.44
#Mann= 3 ,-1 , 0
       0     .12       0   79.83    .045       0   97.08     .12       0
Bank Sta=79.83,97.08
XS Rating Curve= 0 ,0
Exp/Cntr=0.3,0.1

Type RM Length L Ch R = 1 ,4088.8  ,88,88.4,88.7
XS GIS Cut Line= 3
     1815346.378      183221.732     1815508.271      183144.215
     1815567.994       183132.41
#Sta/Elev= 20
       0 1904.11    18.9 1898.89    28.3 1896.09    47.2 1890.19    56.7  1887.4
    66.1 1885.12    75.6 1883.54    94.5 1881.65   103.9 1879.88   113.4 1877.86
  115.971877.633   122.8 1877.03   132.3 1877.55  132.961877.655   141.7 1879.05
   160.6 1882.36   179.5 1885.24   188.2 1886.68   205.6 1889.68   240.4 1895.93
#Mann= 3 ,-1 , 0
       0     .12       0  115.97    .045       0  132.96     .12       0
Bank Sta=115.97,132.96
XS Rating Curve= 0 ,0
Exp/Cntr=0.3,0.1

Type RM Length L Ch R = 1 ,4000.4  ,86.7,82.5,77.6
XS GIS Cut Line= 2
     1815387.735      183294.568     1815588.132      183199.077
#Sta/Elev= 27
       0  1898.5     9.6 1895.84    19.3 1893.42      29 1891.16    38.6 1888.94
    48.3 1886.78    57.9 1884.66    67.6 1882.39    77.2 1879.55    86.5  1877.1
    86.9 1876.99      91 1876.52    96.5 1875.89   101.5 1876.23   106.2 1876.54
   115.8  1877.6   125.5 1878.34   135.1 1879.62   144.8  1882.5   154.4 1885.74
   164.1 1887.77   173.7 1888.95   183.4 1890.11     193  1891.4   202.7 1892.77
   212.3 1894.32     222 1896.16
#Mann= 3 ,-1 , 0
       0     .12       0      91    .045       0   106.2     .12       0
Bank Sta=91,106.2
XS Rating Curve= 0 ,0
Exp/Cntr=0.3,0.1