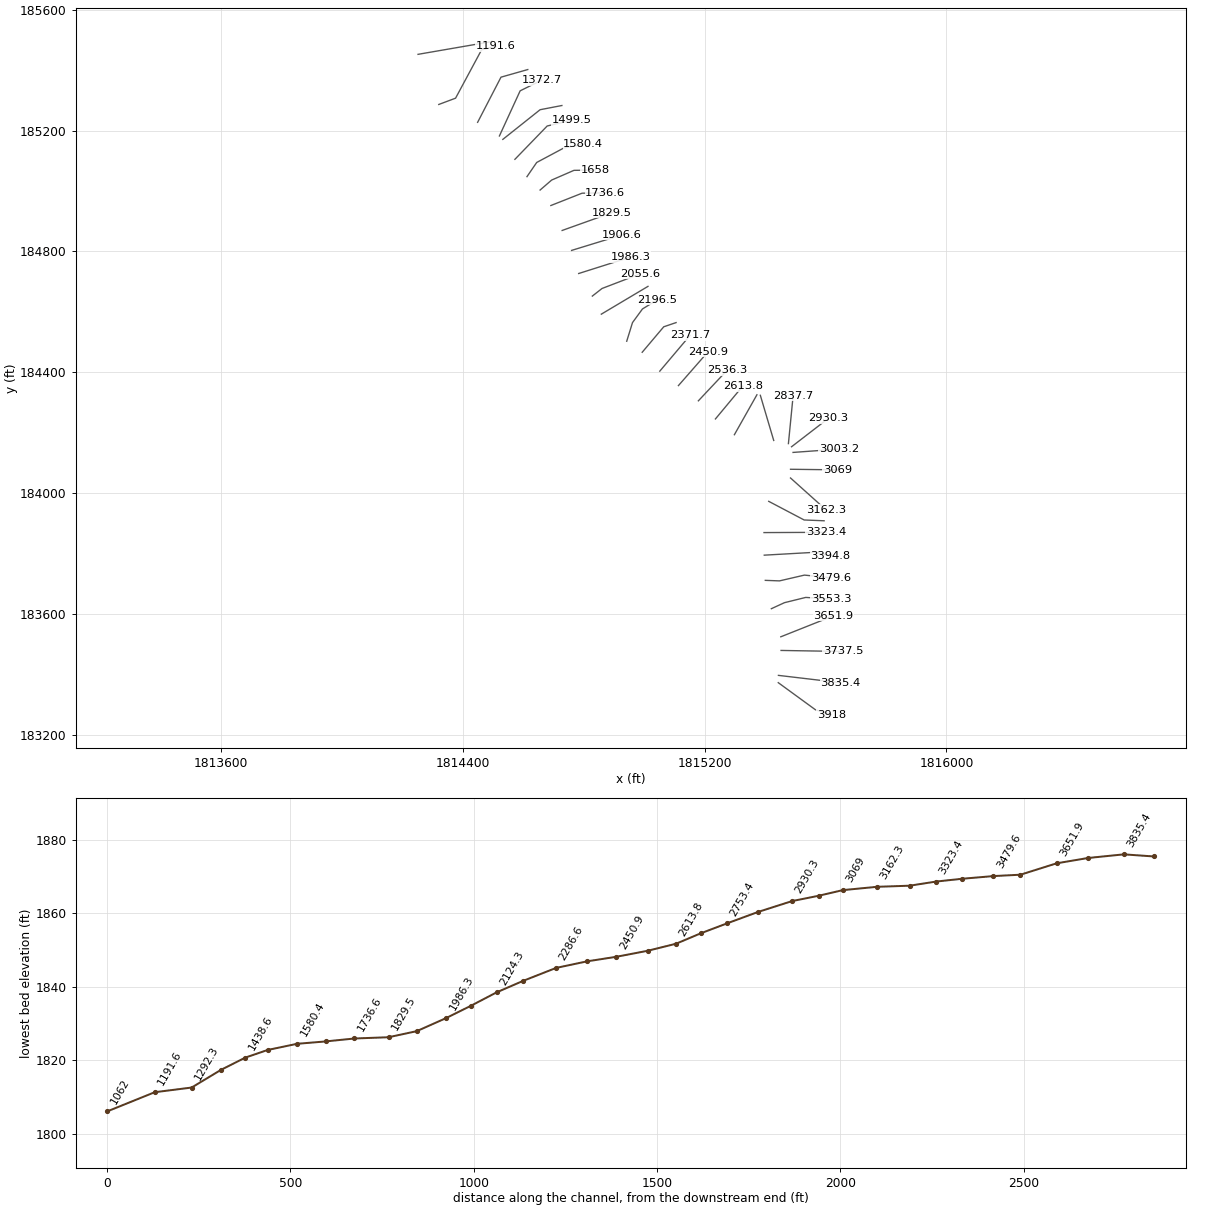
HEC-RAS study HANGINGRN.prj: HANGINGRN

--- HANGINGRN.g01 (geometry) --- (continued)

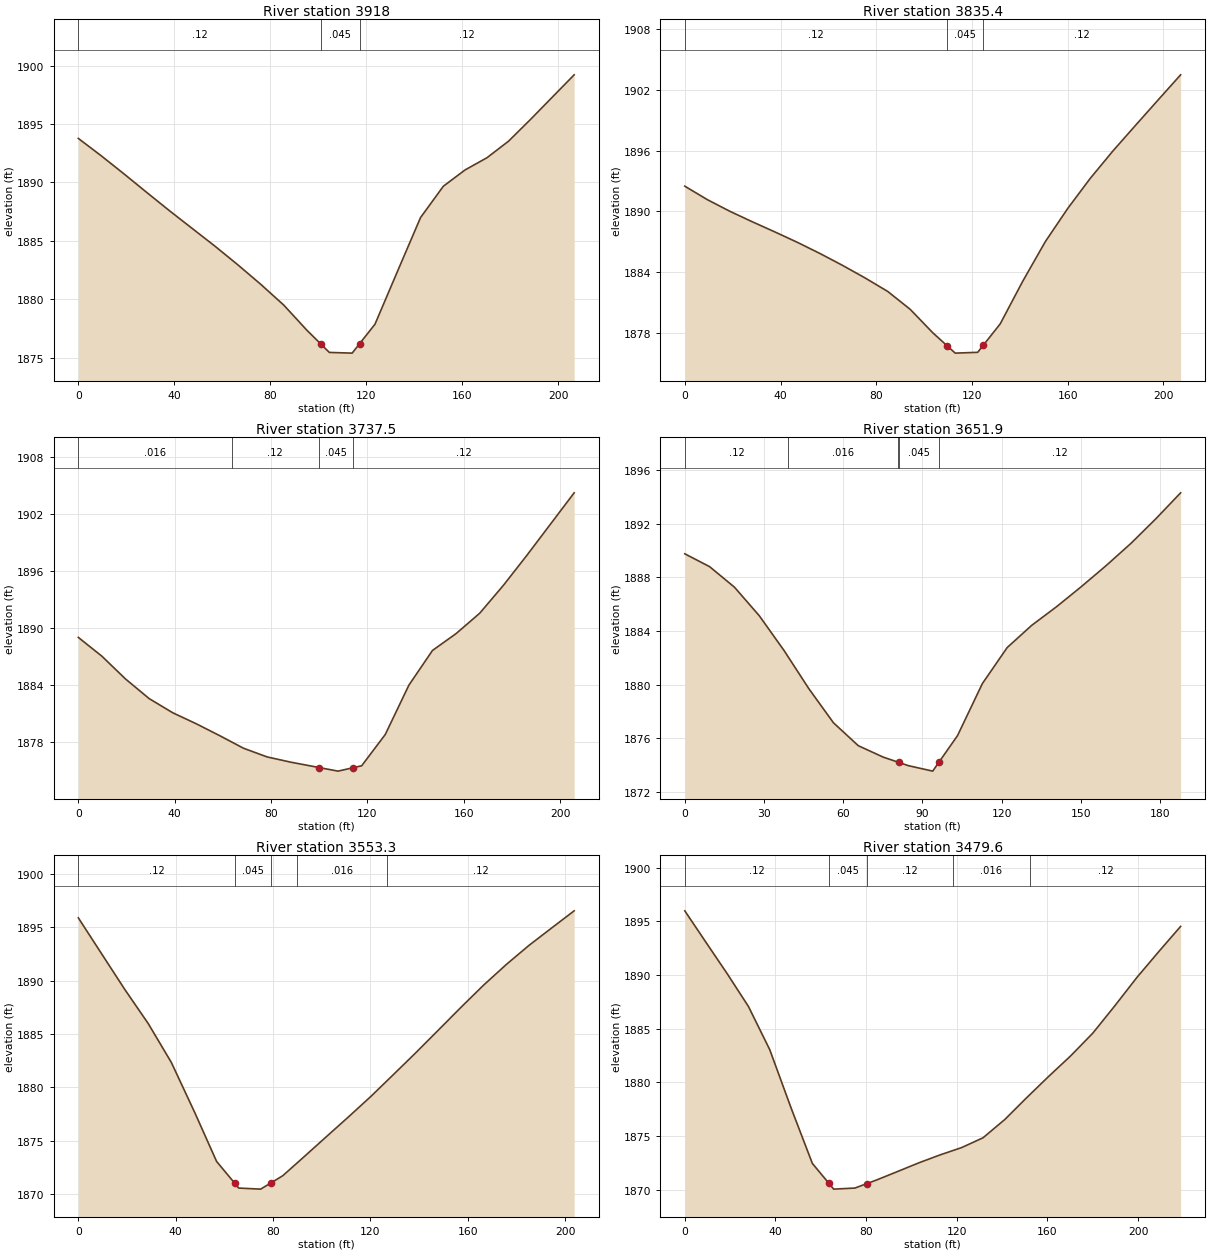
Type RM Length L Ch R = 1 ,3918    ,70.8,82.5,94.2
XS GIS Cut Line= 3
     1815443.688      183374.077     1815566.605      183284.493
     1815618.688      183268.521
#Sta/Elev= 27
       0 1893.77     9.5 1892.29      19 1890.74    28.5 1889.15      38 1887.58
    47.5 1886.06      57 1884.54    66.5 1882.95      76 1881.29    85.6 1879.51
    95.1 1877.39  100.951876.199   103.4  1875.7   104.6 1875.46   114.1  1875.4
   117.21876.208   118.4 1876.52   123.6 1877.87   133.1 1882.45   142.6    1887
   152.1 1889.68   161.2 1891.08   170.3 1892.12   179.3 1893.54   188.4 1895.39
   197.5  1897.3   206.6 1899.21
#Mann= 3 ,-1 , 0
       0     .12       0  100.95    .045       0   117.2     .12       0
Bank Sta=100.95,117.2
XS Rating Curve= 0 ,0
Exp/Cntr=0.3,0.1

Type RM Length L Ch R = 1 ,3835.4  ,95.2,97.9,99
XS GIS Cut Line= 2
     1815444.252      183398.209     1815649.981      183373.903
#Sta/Elev= 25
       0 1892.49     9.4 1891.16    18.8 1890.01    28.2 1888.97    37.7 1887.96
    47.1 1886.93    56.5 1885.83    65.9 1884.66    75.3 1883.42    84.8 1882.08
    94.2 1880.31   103.6    1878   109.7 1876.69     113 1875.98   122.4 1876.06
   124.7 1876.75   131.8 1878.87   141.2 1883.08   150.7 1887.02   160.1 1890.31
   169.5 1893.28   178.9 1895.97   188.3 1898.49   197.7 1900.99   207.2  1903.5
#Mann= 3 ,-1 , 0
       0     .12       0   109.7    .045       0   124.7     .12       0
Bank Sta=109.7,124.7
XS Rating Curve= 0 ,0
Exp/Cntr=0.3,0.1

Type RM Length L Ch R = 1 ,3737.5  ,76.6,85.6,95.4
XS GIS Cut Line= 2
     1815452.933      183480.674     1815658.662      183477.202
#Sta/Elev= 27
       0 1889.04     9.8 1887.06    19.6 1884.67    29.4 1882.61    39.2 1881.12
      49 1879.96    58.8  1878.7   63.59 1878.06    68.6 1877.39    78.4 1876.48
    88.2 1875.93      98 1875.46   99.871875.369   101.5 1875.29   107.8 1874.99
  114.07 1875.35   116.5 1875.49   117.6 1875.55   127.4 1878.84   137.2 1884.02
     147 1887.67   156.8 1889.44   166.6 1891.58   176.4  1894.5   186.2 1897.67
     196 1900.95   205.8 1904.23
#Mann= 4 ,-1 , 0
       0    .016       0   63.59     .12       0   99.87    .045       0
  114.07     .12       0
Bank Sta=99.87,114.07
XS Rating Curve= 0 ,0
Exp/Cntr=0.3,0.1

Type RM Length L Ch R = 1 ,3651.9  ,101.7,98.7,95.5
XS GIS Cut Line= 2
     1815452.065      183525.813     1815626.544      183595.257
#Sta/Elev= 27
       0 1889.76     9.4  1888.8    18.8 1887.27    28.2 1885.14    37.6 1882.54
   39.241882.043      47 1879.69    56.3 1877.15    65.7 1875.44    75.1 1874.59
   80.751874.211   81.111874.187    84.5 1873.96    85.1 1873.93    93.9 1873.54
   96.231874.198   100.1 1875.29   103.3 1876.19   112.7 1880.07   122.1 1882.76
   131.4 1884.42   140.8 1885.81   150.2 1887.31   159.6 1888.88     169 1890.54
   178.4 1892.37   187.8 1894.31
#Mann= 5 ,-1 , 0
       0     .12       0   39.24    .016       0   80.75     .12       0
   81.11    .045       0   96.23     .12       0
Bank Sta=81.11,96.23
XS Rating Curve= 0 ,0
Exp/Cntr=0.3,0.1

Type RM Length L Ch R = 1 ,3553.3  ,74.4,73.7,73.4
XS GIS Cut Line= 4
     1815420.815      183618.695     1815464.218       183638.66
      1815534.53      183656.021     1815617.863      183650.813
#Sta/Elev= 29
       0 1895.89     9.6 1892.51    19.1 1889.17    28.7 1885.98    38.2 1882.33
    47.8 1877.64    56.8 1873.04   64.291870.983    64.7 1870.87    65.9 1870.54
    74.9 1870.44   78.961870.998    79.7  1871.1      84  1871.7   89.971872.914
      93 1873.53   102.1  1875.4   111.2 1877.26   120.2 1879.14  126.671880.573
   129.5  1881.2   138.8 1883.27     148 1885.38   157.3 1887.52   166.6  1889.6
   175.9 1891.53   185.1  1893.3   194.4 1894.93   203.7 1896.55
#Mann= 5 ,-1 , 0
       0     .12       0   64.29    .045       0   78.96     .12       0
   89.97    .016       0  126.67     .12       0
Bank Sta=64.29,78.96
XS Rating Curve= 0 ,0
Exp/Cntr=0.3,0.1

Type RM Length L Ch R = 1 ,3479.6  ,88.1,84.9,80.7
XS GIS Cut Line= 4
     1815400.849      183712.445     1815447.724      183710.709
      1815530.19      183729.806     1815616.995      183721.125
#Sta/Elev= 30
       0 1895.98     9.4 1893.03    18.8  1890.1    28.1 1887.07    37.5 1883.05
    46.9 1877.63    56.3 1872.46    62.1 1870.99   63.651870.594    65.7 1870.07
    75.1 1870.17    77.1 1870.33   80.461870.593    84.5 1870.91    93.9 1871.71
   103.3 1872.52   112.7 1873.26  118.181873.652   122.2 1873.94   131.6 1874.85
   141.2 1876.55   150.9 1878.59  152.481878.912   160.6 1880.57   170.3 1882.48
     180 1884.58   189.7 1887.12   199.4 1889.75   209.1 1892.17   218.8 1894.53
#Mann= 5 ,-1 , 0
       0     .12       0   63.65    .045       0   80.46     .12       0
  118.18    .016       0  152.48     .12       0
Bank Sta=63.65,80.46
XS Rating Curve= 0 ,0
Exp/Cntr=0.3,0.1

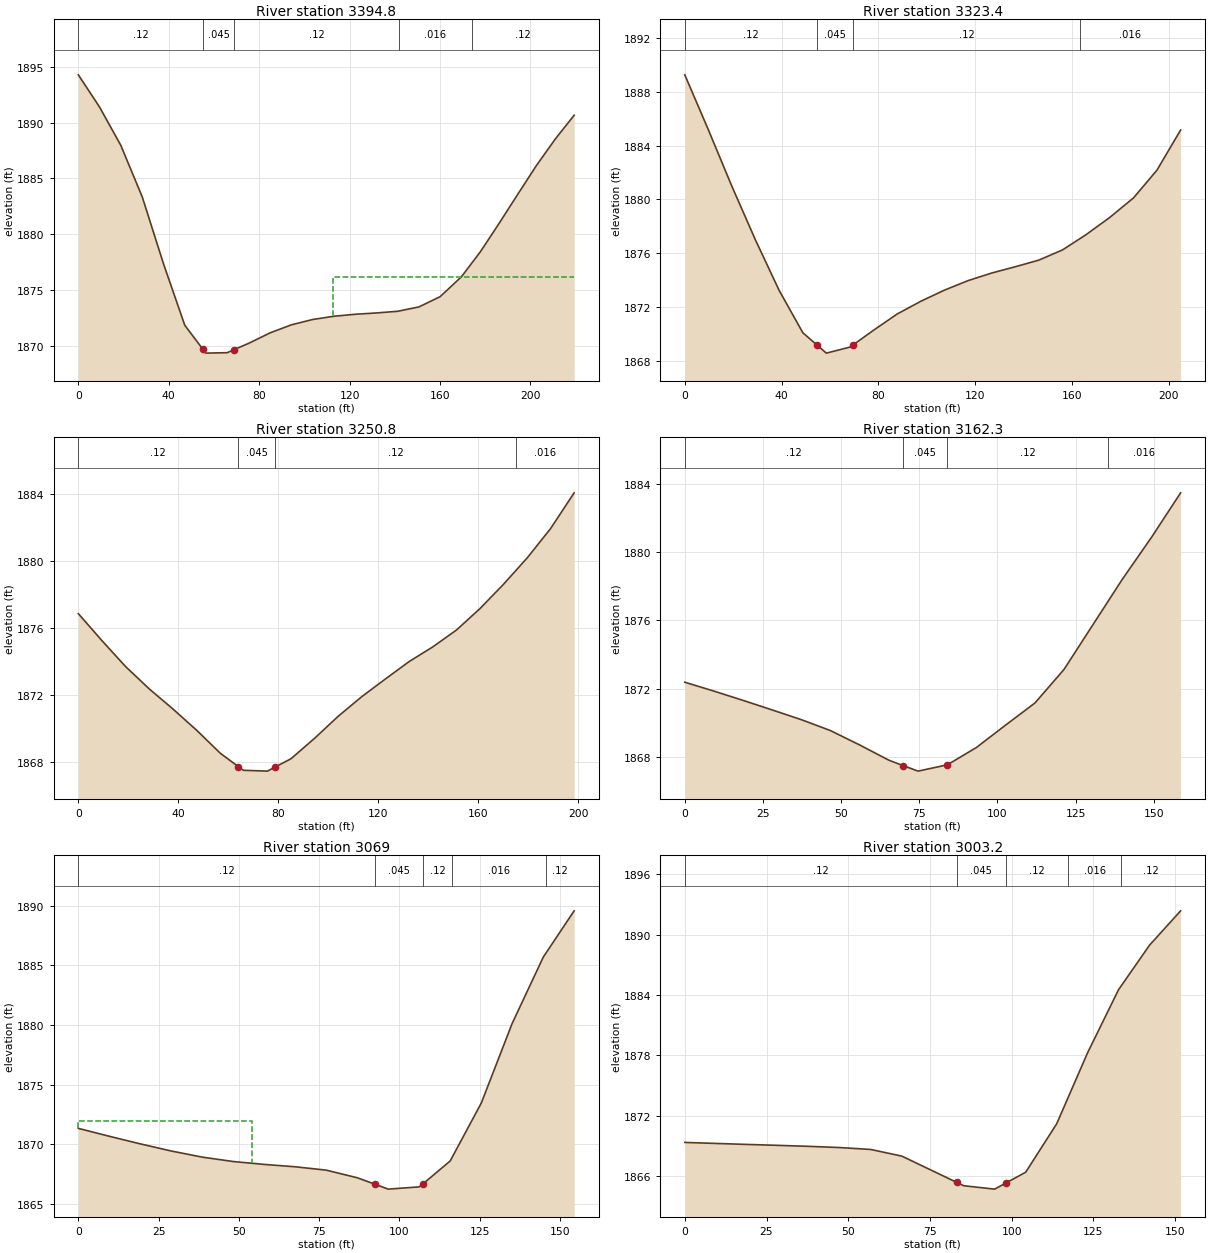
Type RM Length L Ch R = 1 ,3394.8  ,72.5,71.3,70.2
XS GIS Cut Line= 3
     1815397.377      183795.778     1815566.648      183805.327
     1815615.259      183794.042
#Sta/Elev= 30
       0 1894.28     9.4 1891.39    18.8 1887.96    28.3 1883.33    37.7 1877.34
    47.1 1871.84   55.161869.673    56.4 1869.34    65.9 1869.38   69.021869.658
    71.4 1869.87    75.4 1870.22    84.8 1871.15    94.2 1871.87   103.6 1872.35
     113 1872.64   122.4 1872.82   131.9 1872.94   141.3 1873.09  141.751873.109
   150.7 1873.48   160.1  1874.4   169.5 1876.18     174 1877.38   177.9 1878.42
   186.2 1880.97   194.5 1883.59   202.8 1886.18   211.1 1888.54   219.4 1890.66
#Mann= 5 ,-1 , 0
       0     .12       0   55.16    .045       0   69.02     .12       0
  141.75    .016       0     174     .12       0
#XS Ineff= 2 , 0
                          112.49         1876.15
Permanent Ineff=
       F       F
Bank Sta=55.16,69.02
XS Rating Curve= 0 ,0
Exp/Cntr=0.3,0.1

Type RM Length L Ch R = 1 ,3323.4  ,83.6,72.6,61.5
XS GIS Cut Line= 2
     1815396.509      183870.431      1815601.37      183871.299
#Sta/Elev= 27
       0 1889.26     9.8 1885.15    19.5 1880.96    29.3 1876.95      39 1873.24
    48.8 1870.09   54.471869.205    55.4 1869.06    58.5 1868.58    68.3 1869.03
   69.641869.202    70.4  1869.3      78 1870.28    87.8 1871.49    97.6 1872.44
   107.3 1873.26   117.1 1873.97   126.8 1874.53   136.6    1875   146.3 1875.49
   156.1 1876.25  163.331877.092   165.8 1877.38   175.6 1878.66   185.4 1880.11
   195.1 1882.17   204.9 1885.16
#Mann= 4 ,-1 , 0
       0     .12       0   54.47    .045       0   69.64     .12       0
  163.33    .016       0
Bank Sta=54.47,69.64
XS Rating Curve= 0 ,0
Exp/Cntr=0.3,0.1

Type RM Length L Ch R = 1 ,3250.8  ,94.1,88.5,82.9
XS GIS Cut Line= 3
     1815412.134      183973.729     1815529.322      183912.097
     1815595.294      183909.493
#Sta/Elev= 26
       0 1876.86     9.5 1875.24    18.9  1873.7    28.4 1872.36    37.8 1871.17
    47.3  1869.9    56.8 1868.52   63.991867.723      66  1867.5    75.7 1867.45
   78.691867.687      81 1867.87    85.1 1868.19    94.6 1869.42     104 1870.73
   113.5 1871.91     123 1872.97   132.4    1874   141.8 1874.87   151.3 1875.88
   160.7 1877.16   170.1 1878.61  175.171879.453   179.6 1880.19     189 1881.95
   198.4 1884.08
#Mann= 4 ,-1 , 0
       0     .12       0   63.99    .045       0   78.69     .12       0
  175.17    .016       0
Bank Sta=63.99,78.69
XS Rating Curve= 0 ,0
Exp/Cntr=0.3,0.1

Type RM Length L Ch R = 1 ,3162.3  ,76.1,93.4,110.6
XS GIS Cut Line= 2
     1815484.183      184050.986     1815602.238      183945.084
#Sta/Elev= 21
       0 1872.37     9.3 1871.85    18.7  1871.3      28 1870.74    37.3 1870.17
    46.6 1869.53      56 1868.68    65.3 1867.79    69.9 1867.47    74.6 1867.15
      84 1867.52    84.9 1867.62    93.3 1868.54   102.6 1869.85     112 1871.15
   121.3 1873.12   130.6 1875.76  135.351877.108   139.9  1878.4   149.3 1880.88
   158.6 1883.49
#Mann= 4 ,-1 , 0
       0     .12       0    69.9    .045       0      84     .12       0
  135.35    .016       0
Bank Sta=69.9,84
XS Rating Curve= 0 ,0
Exp/Cntr=0.3,0.1

Type RM Length L Ch R = 1 ,3069    ,64.2,65.8,66.9
XS GIS Cut Line= 2
      1815484.27      184079.806     1815638.697      184077.896
#Sta/Elev= 23
       0 1871.34     9.6 1870.68    19.3 1870.04      29 1869.44    38.6 1868.93
    48.3 1868.56    57.9 1868.32    67.6 1868.12    77.2 1867.84    86.9  1867.2
   92.39 1866.66    93.2 1866.58    96.5 1866.25   106.2 1866.44  107.221866.669
   108.2 1866.89   115.8 1868.61  116.441868.931   125.5 1873.47   135.1 1880.13
   144.8 1885.69  145.731886.065   154.4 1889.56
#Mann= 5 ,-1 , 0
       0     .12       0   92.39    .045       0  107.22     .12       0
  116.44    .016       0  145.73     .12       0
#XS Ineff= 2 , 0
           53.99 1871.97
Permanent Ineff=
       F       F
Bank Sta=92.39,107.22
XS Rating Curve= 0 ,0
Exp/Cntr=0.3,0.1

Type RM Length L Ch R = 1 ,3003.2  ,59.7,72.9,86.2
XS GIS Cut Line= 2
     1815492.603      184135.535     1815643.905      184146.472
#Sta/Elev= 21
       0 1869.36     9.5 1869.26      19 1869.16    28.4 1869.07    37.9 1868.97
    47.4 1868.85    56.9 1868.66    66.4    1868    75.8 1866.54    83.2 1865.39
    85.3 1865.06    94.8 1864.72    98.2 1865.32   104.3  1866.4   113.8 1871.22
  117.181873.744   123.2 1878.24   132.7 1884.53  133.591884.945   142.2 1888.96
   151.7 1892.37
#Mann= 5 ,-1 , 0
       0     .12       0    83.2    .045       0    98.2     .12       0
  117.18    .016       0  133.59     .12       0
Bank Sta=83.2,98.2
XS Rating Curve= 0 ,0
Exp/Cntr=0.3,0.1

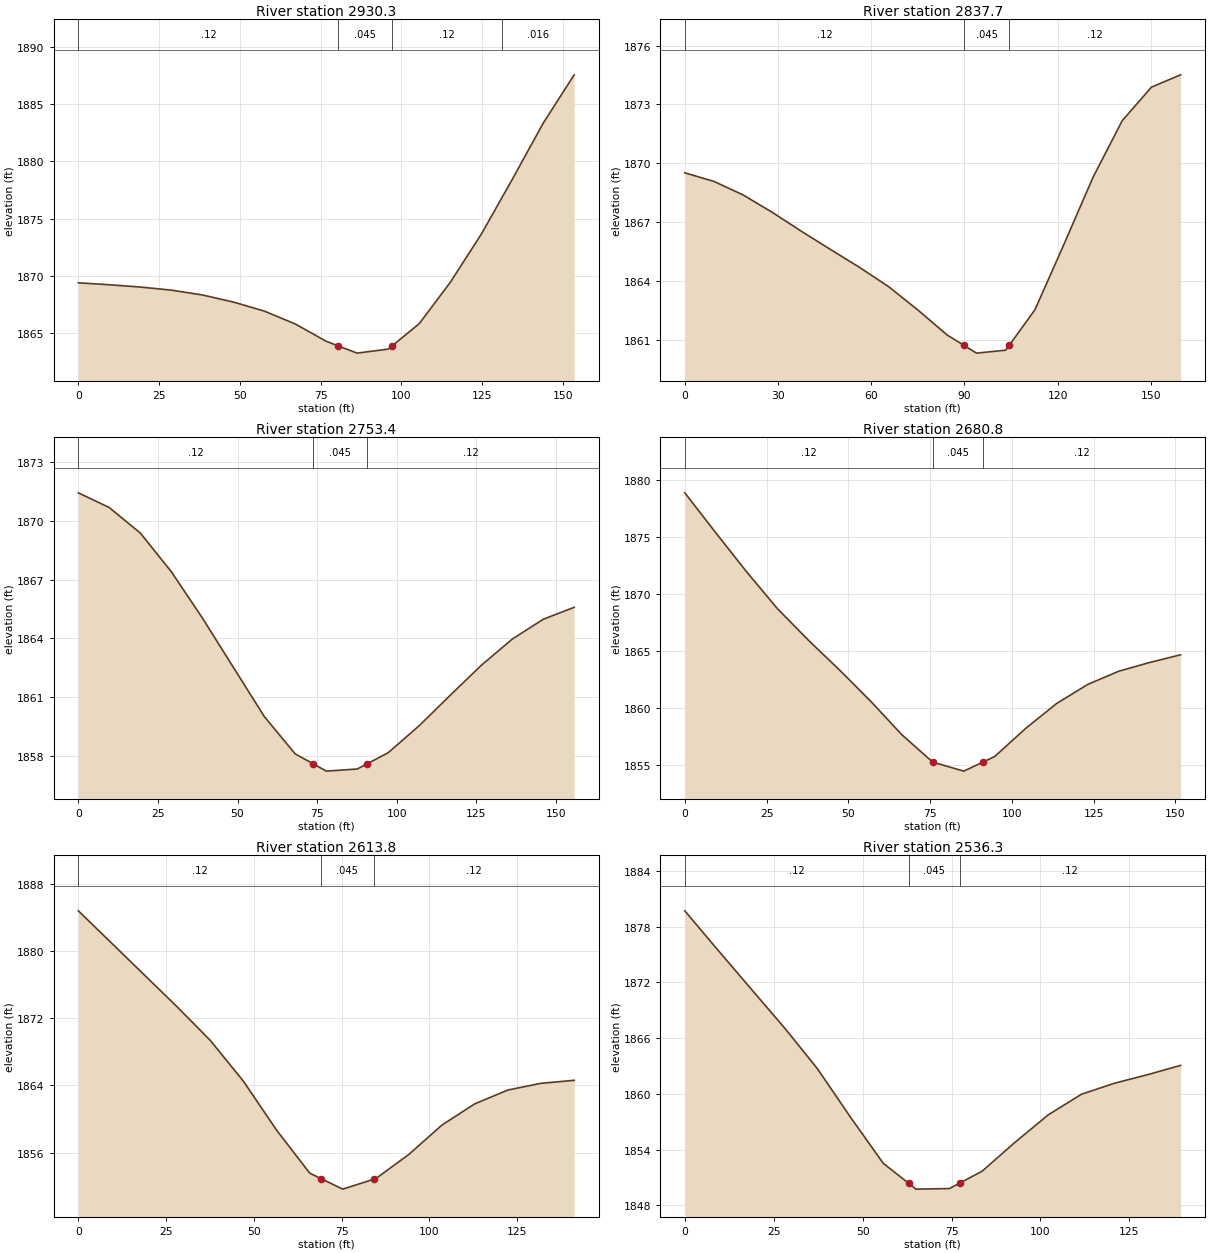
Type RM Length L Ch R = 1 ,2930.3  ,73.9,92.6,111.7
XS GIS Cut Line= 2
     1815487.655      184154.285     1815609.183      184248.035
#Sta/Elev= 22
       0  1869.4     9.6 1869.23    19.2 1869.03    28.8 1868.76    38.4 1868.34
      48 1867.72    57.6 1866.93    67.2  1865.8    76.7  1864.3   80.531863.884
    83.6 1863.55    86.3 1863.26    95.9 1863.61   97.141863.895    98.6 1864.23
   105.5 1865.82   115.1 1869.42   124.7 1873.62  131.161876.843   134.3 1878.41
   143.9 1883.33   153.5 1887.56
#Mann= 4 ,-1 , 0
       0     .12       0   80.53    .045       0   97.14     .12       0
  131.16    .016       0
Bank Sta=80.53,97.14
XS Rating Curve= 0 ,0
Exp/Cntr=0.3,0.1

Type RM Length L Ch R = 1 ,2837.7  ,75.3,84.2,92.7
XS GIS Cut Line= 2
     1815477.238      184164.702     1815492.863      184323.556
#Sta/Elev= 21
       0 1869.51     9.4 1869.07    18.8 1868.38    28.2 1867.49    37.6 1866.52
      47 1865.59    56.3 1864.68    65.7 1863.69    75.1  1862.5    84.5 1861.23
    88.3 1860.86   89.911860.702    93.9 1860.31   103.3 1860.46  104.44 1860.71
   112.7 1862.52   122.1 1865.88   131.4 1869.28   140.8 1872.17   150.2 1873.88
   159.6 1874.51
#Mann= 3 ,-1 , 0
       0     .12       0   89.91    .045       0  104.44     .12       0
Bank Sta=89.91,104.44
XS Rating Curve= 0 ,0
Exp/Cntr=0.3,0.1

Type RM Length L Ch R = 1 ,2753.4  ,90.7,72.6,53.6
XS GIS Cut Line= 2
     1815428.627      184175.118     1815384.356      184324.424
#Sta/Elev= 21
       0 1871.44     9.7 1870.69    19.5 1869.38    29.2 1867.41    38.9 1865.06
    48.7 1862.52    58.4 1860.01    68.1  1858.1    71.8 1857.77   73.791857.591
    77.9 1857.22    86.8 1857.32    87.6 1857.33   90.561857.583    97.3 1858.16
   107.1 1859.55   116.8  1861.1   126.5 1862.62   136.3 1863.97     146 1864.98
   155.7 1865.59
#Mann= 3 ,-1 , 0
       0     .12       0   73.79    .045       0   90.56     .12       0
Bank Sta=73.79,90.56
XS Rating Curve= 0 ,0
Exp/Cntr=0.3,0.1

Type RM Length L Ch R = 1 ,2680.8  ,70.9,67,62.8
XS GIS Cut Line= 2
     1815298.571       184194.09     1815373.072       184326.16
#Sta/Elev= 20
       0 1878.88     9.5 1875.37      19 1871.92    28.4  1868.7    37.9 1865.93
    47.4 1863.32    56.9 1860.59    66.3 1857.69    74.9  1855.5    75.8 1855.27
    85.3 1854.48    89.9  1855.1   91.151855.271    94.8 1855.77   104.2 1858.22
   113.7 1860.41   123.2 1862.08   132.7 1863.24   142.2 1864.01   151.6 1864.68
#Mann= 3 ,-1 , 0
       0     .12       0    75.8    .045       0   91.15     .12       0
Bank Sta=75.8,91.15
XS Rating Curve= 0 ,0
Exp/Cntr=0.3,0.1

Type RM Length L Ch R = 1 ,2613.8  ,78.9,77.5,76.2
XS GIS Cut Line= 2
     1815235.919      184246.299     1815326.197      184354.806
#Sta/Elev= 18
       0 1884.78     9.4 1880.97    18.8 1877.15    28.2 1873.33    37.6 1869.35
      47 1864.51    56.5 1858.66    65.9 1853.56    69.1 1852.91    75.3 1851.66
    84.1 1852.83    84.7 1852.91    94.1 1855.78   103.5 1859.27   112.9 1861.81
   122.3 1863.45   131.7 1864.25   141.2 1864.61
#Mann= 3 ,-1 , 0
       0     .12       0    69.1    .045       0    84.1     .12       0
Bank Sta=69.1,84.1
XS Rating Curve= 0 ,0
Exp/Cntr=0.3,0.1

Type RM Length L Ch R = 1 ,2536.3  ,84.5,85.4,86.1
XS GIS Cut Line= 2
     1815179.495      184306.195     1815274.981      184407.757
#Sta/Elev= 20
       0  1879.7     9.3 1875.48    18.6 1871.31    27.9 1867.16    37.2 1862.75
    46.5 1857.53    55.8 1852.52    61.3 1850.86    62.91850.376      65 1849.74
    74.4  1849.8    76.3 1850.19    77.31850.393    83.6 1851.67    92.9  1854.8
   102.2 1857.74   111.5 1859.95   120.8 1861.14   130.1 1862.06   139.4 1863.06
#Mann= 3 ,-1 , 0
       0     .12       0    62.9    .045       0    77.3     .12       0
Bank Sta=62.9,77.3
XS Rating Curve= 0 ,0
Exp/Cntr=0.3,0.1

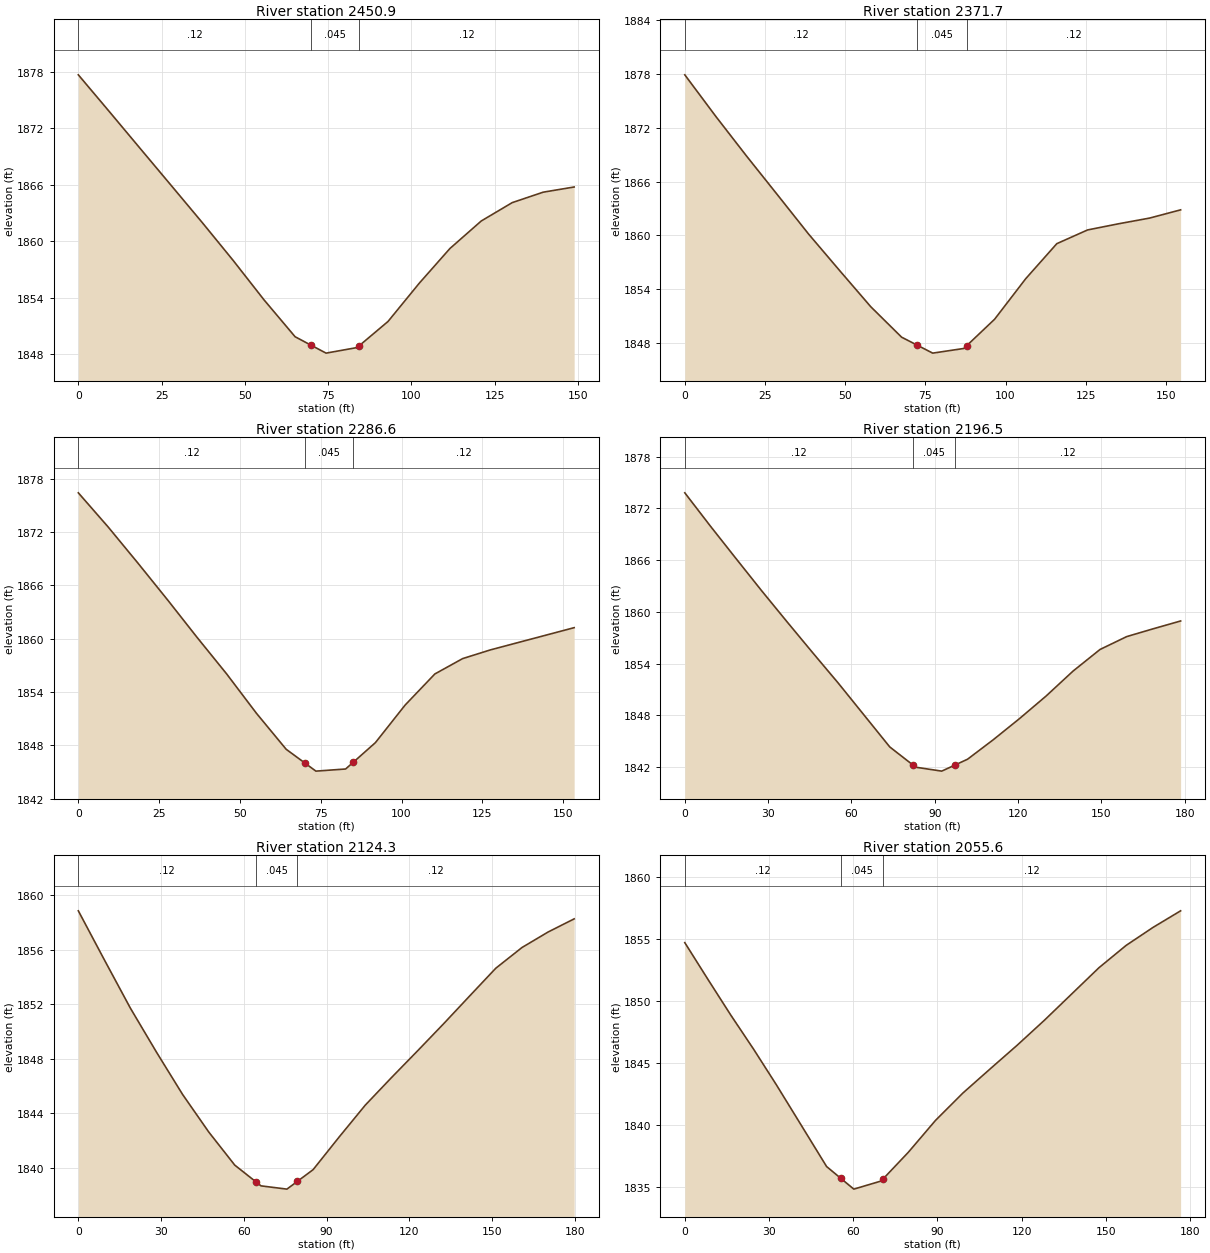
Type RM Length L Ch R = 1 ,2450.9  ,78.8,79.2,79.6
XS GIS Cut Line= 2
     1815113.523      184356.542     1815211.613      184468.521
#Sta/Elev= 20
       0 1877.66     9.3 1873.76    18.6 1869.83    27.9 1865.91    37.2 1861.98
    46.5 1857.95    55.8 1853.75    65.1 1849.85    69.3 1849.06   69.941848.941
    74.4 1848.11    83.7  1848.7    84.3 1848.88      93 1851.47   102.4 1855.54
   111.6 1859.22     121 1862.14   130.3 1864.09   139.6  1865.2   148.9 1865.75
#Mann= 3 ,-1 , 0
       0     .12       0   69.94    .045       0    84.3     .12       0
Bank Sta=69.94,84.3
XS Rating Curve= 0 ,0
Exp/Cntr=0.3,0.1

Type RM Length L Ch R = 1 ,2371.7  ,85.1,85.1,85.1
XS GIS Cut Line= 2
     1815051.891      184404.285     1815151.718       184522.34
#Sta/Elev= 21
       0 1877.92     9.7 1873.27    19.3 1868.84      29 1864.49    38.6 1860.16
    48.3 1856.08      58 1852.05    67.6 1848.66   72.431847.773    73.7 1847.54
    77.3 1846.88      87  1847.4   87.941847.721    88.7 1847.98    96.6 1850.66
   106.3 1855.18     116 1859.09   125.6 1860.62   135.3 1861.31   144.9 1861.94
   154.6 1862.86
#Mann= 3 ,-1 , 0
       0     .12       0   72.43    .045       0   87.94     .12       0
Bank Sta=72.43,87.94
XS Rating Curve= 0 ,0
Exp/Cntr=0.3,0.1

Type RM Length L Ch R = 1 ,2286.6  ,88.5,90.1,91.7
XS GIS Cut Line= 3
     1814993.731      184466.785     1815064.912      184550.986
     1815105.711      184564.875
#Sta/Elev= 20
       0 1876.39     9.2 1872.56    18.4  1868.5    27.6 1864.35    36.8  1860.1
    45.9 1856.01    55.1 1851.59    64.3 1847.54    70.1 1845.99    73.5 1845.08
    82.7 1845.32    85.1 1846.09    91.9 1848.28   101.1 1852.51   110.3 1856.01
   118.9 1857.74   127.5 1858.72   136.1 1859.55   144.7 1860.38   153.4 1861.22
#Mann= 3 ,-1 , 0
       0     .12       0    70.1    .045       0    85.1     .12       0
Bank Sta=70.1,85.1
XS Rating Curve= 0 ,0
Exp/Cntr=0.3,0.1

Type RM Length L Ch R = 1 ,2196.5  ,81.3,72.2,63
XS GIS Cut Line= 4
     1814942.516      184503.243     1814961.613      184564.875
     1814994.599      184610.014     1815044.079      184640.396
#Sta/Elev= 22
       0  1873.8     9.2 1869.95    18.4  1866.2    27.6 1862.48    36.9 1858.82
    46.1 1855.25    55.3 1851.73    64.5 1848.06    73.8 1844.35    82.3 1842.22
    83.2    1842    92.5 1841.55    97.3 1842.26   101.8 1842.93   111.1  1845.2
   120.4 1847.61   130.1 1850.26   139.8 1853.15   149.5 1855.65   159.1 1857.14
   168.8 1858.06   178.5 1858.95
#Mann= 3 ,-1 , 0
       0     .12       0    82.3    .045       0    97.3     .12       0
Bank Sta=82.3,97.3
XS Rating Curve= 0 ,0
Exp/Cntr=0.3,0.1

Type RM Length L Ch R = 1 ,2124.3  ,72.4,68.7,64.8
XS GIS Cut Line= 2
     1814858.464      184592.742     1815012.829      184684.667
#Sta/Elev= 22
       0 1858.84     9.5 1855.22    18.9 1851.69    28.4 1848.45    37.8 1845.37
    47.3 1842.61    56.7 1840.19    64.4 1838.96    66.2 1838.67    75.6 1838.43
    79.4    1839    85.1 1839.86    94.6 1842.27     104 1844.59   113.5 1846.61
   122.9 1848.56   132.4 1850.56   141.8 1852.59   151.3 1854.63   160.8 1856.15
   170.2 1857.28   179.7 1858.25
#Mann= 3 ,-1 , 0
       0     .12       0    64.4    .045       0    79.4     .12       0
Bank Sta=64.4,79.4
XS Rating Curve= 0 ,0
Exp/Cntr=0.3,0.1

Type RM Length L Ch R = 1 ,2055.6  ,70.7,69.3,67.9
XS GIS Cut Line= 3
     1814828.801      184652.549     1814860.919      184677.722
     1814987.655      184726.334
#Sta/Elev= 22
       0 1854.68     8.2 1851.74    16.3 1848.88    24.5 1846.11    32.6 1843.25
    40.8 1840.24    50.5 1836.67    55.5 1835.73    60.2 1834.85    69.9  1835.5
    70.5 1835.64    79.6 1837.81    89.3 1840.38      99 1842.57   108.7 1844.51
   118.4 1846.43   128.1 1848.44   137.8 1850.55   147.5 1852.66   157.2 1854.46
   166.8 1855.91   176.6 1857.24
#Mann= 3 ,-1 , 0
       0     .12       0    55.5    .045       0    70.5     .12       0
Bank Sta=55.5,70.5
XS Rating Curve= 0 ,0
Exp/Cntr=0.3,0.1

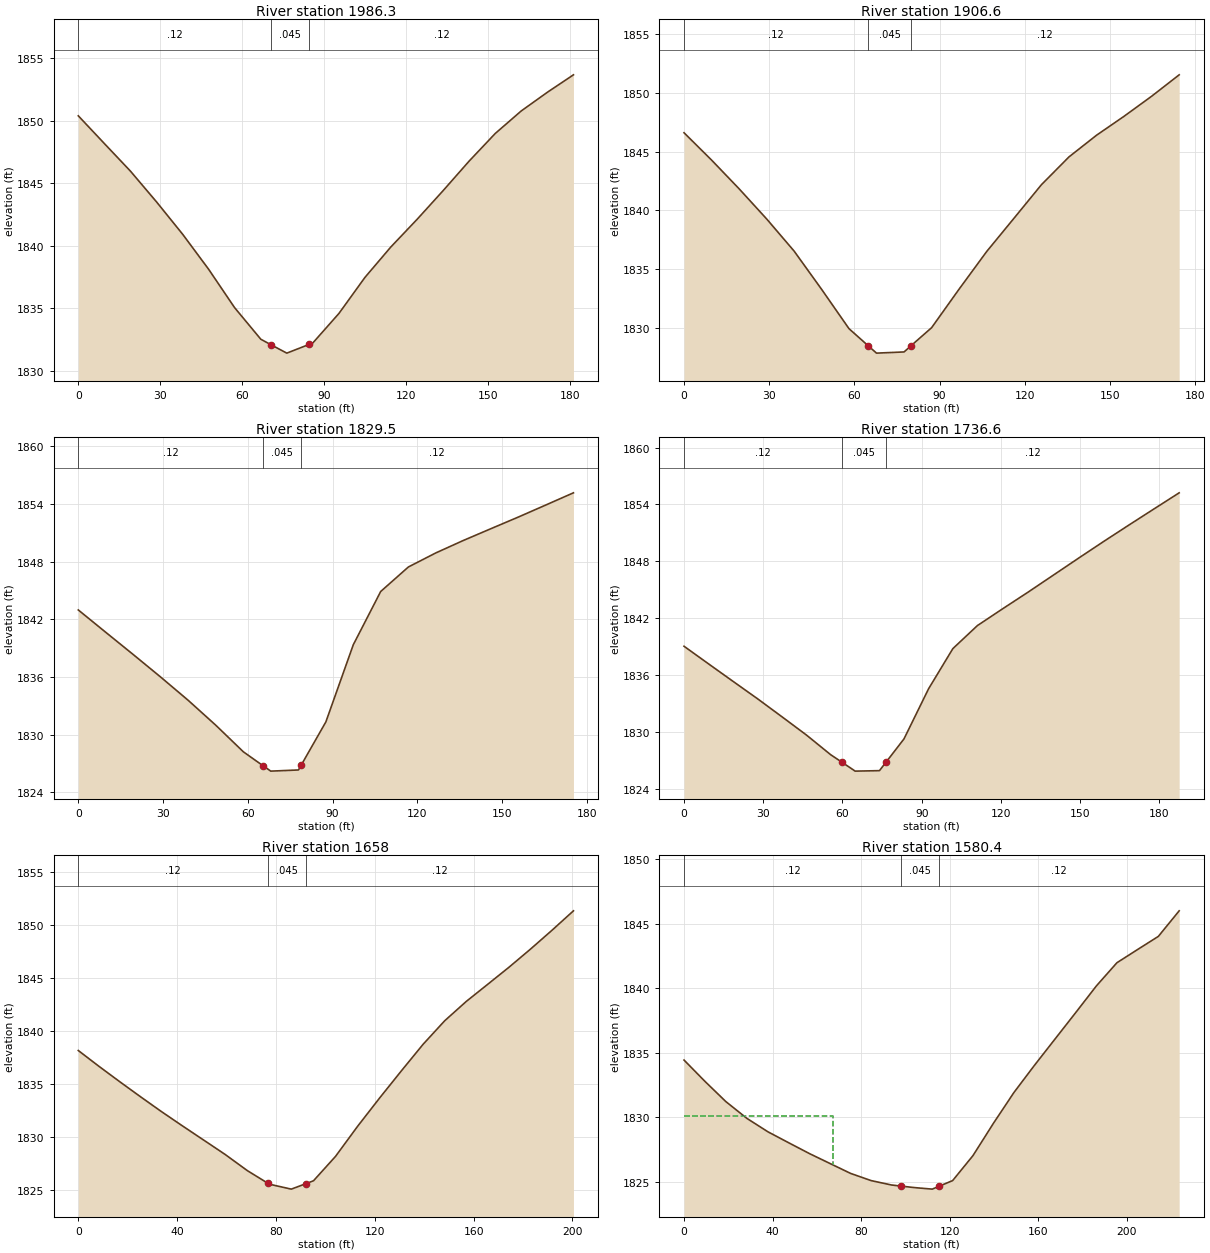
Type RM Length L Ch R = 1 ,1986.3  ,79.7,79.7,79.4
XS GIS Cut Line= 2
     1814783.662      184727.202     1814956.405      184781.889
#Sta/Elev= 24
       0 1850.41     9.5  1848.2    19.1 1845.98    28.6 1843.53    38.2 1840.93
    47.7 1838.13    57.2 1835.06    66.8 1832.53   70.441832.101    71.3    1832
    76.3 1831.42   84.581832.126    85.8 1832.23    86.3 1832.35    95.4  1834.6
   104.9 1837.48   114.4 1839.92     124 1842.13   133.5 1844.42     143 1846.78
   152.6    1849   162.1  1850.8   171.7  1852.3   181.2 1853.69
#Mann= 3 ,-1 , 0
       0     .12       0   70.44    .045       0   84.58     .12       0
Bank Sta=70.44,84.58
XS Rating Curve= 0 ,0
Exp/Cntr=0.3,0.1

Type RM Length L Ch R = 1 ,1906.6  ,75.8,77.1,77.9
XS GIS Cut Line= 2
     1814760.224       184803.59     1814926.891      184854.806
#Sta/Elev= 23
       0  1846.6     9.7 1844.28    19.4 1841.84    29.1 1839.28    38.8 1836.54
    48.4 1833.32    58.1 1829.96   64.871828.506    66.2 1828.22    67.8 1827.88
    77.5 1827.98   80.011828.516    81.2 1828.77    87.2 1830.04    96.9 1833.32
   106.6 1836.51   116.2 1839.33   125.9 1842.19   135.6 1844.55   145.3 1846.39
     155    1848   164.7  1849.7   174.4 1851.52
#Mann= 3 ,-1 , 0
       0     .12       0   64.87    .045       0   80.01     .12       0
Bank Sta=64.87,80.01
XS Rating Curve= 0 ,0
Exp/Cntr=0.3,0.1

Type RM Length L Ch R = 1 ,1829.5  ,92.3,92.9,93.8
XS GIS Cut Line= 2
     1814728.974      184869.563     1814893.905       184928.59
#Sta/Elev= 23
       0 1842.98     9.7 1840.66    19.5 1838.33    29.2 1835.99    38.9 1833.58
    48.7 1830.98    58.4 1828.23    63.4 1827.19   65.381826.781    68.1 1826.22
    77.9 1826.34    78.4  1826.6   78.881826.847    87.6 1831.34    97.3 1839.36
     107  1844.9   116.8 1847.45   126.5 1848.91   136.2  1850.2     146 1851.43
   155.7 1852.64   165.4 1853.89   175.2 1855.16
#Mann= 3 ,-1 , 0
       0     .12       0   65.38    .045       0   78.88     .12       0
Bank Sta=65.38,78.88
XS Rating Curve= 0 ,0
Exp/Cntr=0.3,0.1

Type RM Length L Ch R = 1 ,1736.6  ,77.8,78.6,79.3
XS GIS Cut Line= 3
     1814691.648      184952.028     1814794.947      184992.827
     1814871.336      184993.695
#Sta/Elev= 25
       0 1839.05     9.3 1837.19    18.5 1835.36    27.8 1833.52      37 1831.63
    46.3  1829.7    55.5 1827.62   59.881826.803    62.9 1826.24    64.8 1825.88
      74 1825.93   76.48 1826.82    77.9 1827.33    83.3 1829.28    92.6 1834.56
   101.8  1838.8   111.1 1841.23   120.6 1842.99   130.2 1844.74   139.7 1846.52
   149.3 1848.32   158.8 1850.08   168.4 1851.82   177.9 1853.52   187.5 1855.23
#Mann= 3 ,-1 , 0
       0     .12       0   59.88    .045       0   76.48     .12       0
Bank Sta=59.88,76.48
XS Rating Curve= 0 ,0
Exp/Cntr=0.3,0.1

Type RM Length L Ch R = 1 ,1658    ,75.8,77.6,79.4
XS GIS Cut Line= 4
     1814656.058      185003.243     1814694.252      185036.229
     1814768.037      185068.347     1814837.481      185069.215
#Sta/Elev= 28
       0 1838.17     8.4 1836.67    16.8 1835.22    25.2  1833.8    33.6 1832.41
    42.1 1831.06    50.5 1829.75    59.4 1828.36    68.4 1826.83   76.831825.618
    77.3 1825.55    78.2  1825.5    86.2 1825.08   92.141825.598    93.2 1825.69
    95.2 1825.87   104.1 1828.17   113.1 1831.03     122  1833.7   130.9 1836.29
   139.6 1838.77   148.3 1840.98     157  1842.8   165.7 1844.42   174.4 1846.05
     183 1847.74   191.7 1849.52   200.4 1851.36
#Mann= 3 ,-1 , 0
       0     .12       0   76.83    .045       0   92.14     .12       0
Bank Sta=76.83,92.14
XS Rating Curve= 0 ,0
Exp/Cntr=0.3,0.1

Type RM Length L Ch R = 1 ,1580.4  ,73.8,80.9,87.9
XS GIS Cut Line= 4
     1814612.655      185047.514     1814644.773      185094.389
     1814734.183      185142.132     1814798.419      185154.285
#Sta/Elev= 29
       0 1834.44     9.5 1832.78    18.9 1831.22    28.4 1829.92    37.9 1828.88
    47.4 1828.02    56.8 1827.18      66 1826.42    75.2 1825.66    84.5  1825.1
    93.7 1824.76   98.051824.675   102.9 1824.58   105.3 1824.54   112.1 1824.44
  114.991824.648   120.3 1825.03   121.3  1825.1   130.5 1827.04   139.8 1829.56
     149 1831.93   158.2 1834.02   167.5 1836.06   176.9 1838.12   186.2 1840.18
   195.5 1841.98   204.9 1843.01   214.2 1844.02   223.6    1846
#Mann= 3 ,-1 , 0
       0     .12       0   98.05    .045       0  114.99     .12       0
#XS Ineff= 2 , 0
           67.08 1830.14
Permanent Ineff=
       F       F
Bank Sta=98.05,114.99
XS Rating Curve= 0 ,0
Exp/Cntr=0.3,0.1

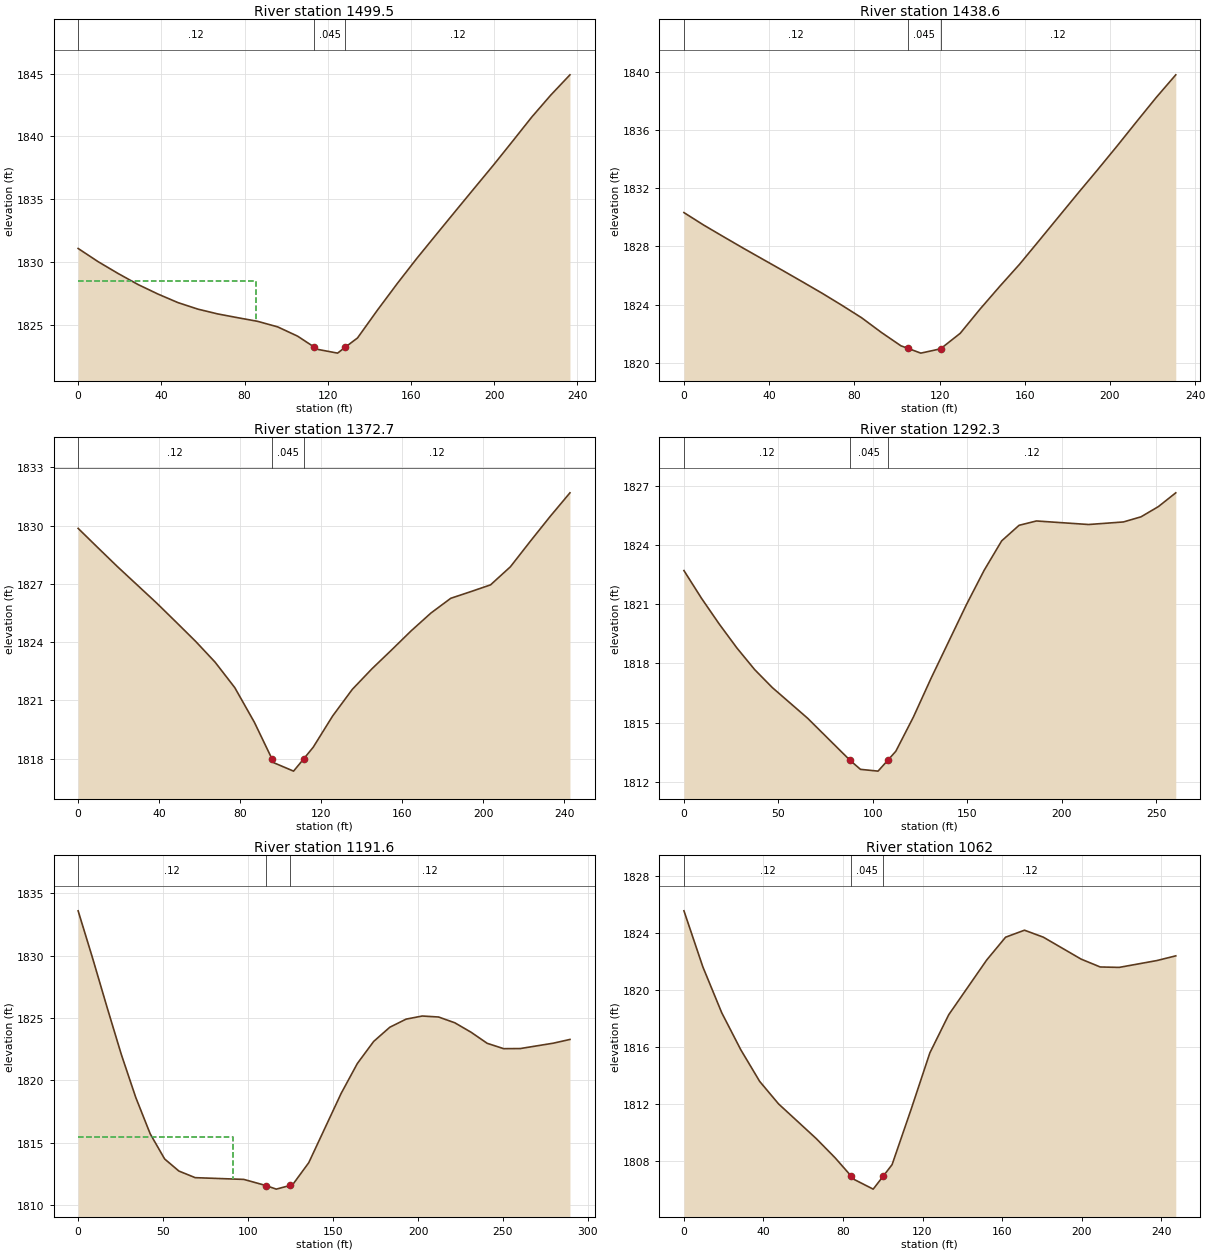
Type RM Length L Ch R = 1 ,1499.5  ,63.8,60.9,57.9
XS GIS Cut Line= 3
     1814572.724      185104.806     1814679.495      185215.049
     1814760.224      185234.146
#Sta/Elev= 28
       0 1831.08     9.6 1830.03    19.2 1829.09    28.8 1828.21    38.4 1827.45
      48 1826.77    57.6 1826.25    67.1 1825.87    76.7 1825.57    86.3 1825.28
    95.9 1824.84   105.5  1824.1   113.4 1823.24   115.1 1823.05   124.7 1822.75
   128.4 1823.22   134.3 1823.96   143.9 1826.18   153.5 1828.31   162.7 1830.27
   171.9 1832.14   181.1    1834   190.3 1835.85   199.6 1837.71   208.8 1839.61
     218 1841.53   227.2 1843.29   236.4  1844.9
#Mann= 3 ,-1 , 0
       0     .12       0   113.4    .045       0   128.4     .12       0
#XS Ineff= 2 , 0
           85.66 1828.53
Permanent Ineff=
       F       F
Bank Sta=113.4,128.4
XS Rating Curve= 0 ,0
Exp/Cntr=0.3,0.1

Type RM Length L Ch R = 1 ,1438.6  ,55.3,65.9,76.4
XS GIS Cut Line= 3
     1814532.794      185170.778     1814656.058      185268.868
     1814728.106      185282.757
#Sta/Elev= 29
       0 1830.32     9.3 1829.46    18.5 1828.67    27.8 1827.88    37.1 1827.11
    46.3 1826.35    55.6 1825.57    64.9 1824.78    74.1 1823.96    83.4  1823.1
    92.7 1822.09   101.9 1821.17   102.5 1821.14  105.221820.993   111.2 1820.67
   117.5 1820.87   120.5 1820.97   129.7 1822.03     139 1823.69   148.3 1825.26
   157.5 1826.76   166.7 1828.39   175.9 1830.03     185 1831.65   194.2 1833.26
   203.4  1834.9   212.6 1836.58   221.7 1838.22   230.9 1839.78
#Mann= 3 ,-1 , 0
       0     .12       0  105.22    .045       0   120.5     .12       0
Bank Sta=105.22,120.5
XS Rating Curve= 0 ,0
Exp/Cntr=0.3,0.1

Type RM Length L Ch R = 1 ,1372.7  ,81.4,80.4,79.3
XS GIS Cut Line= 3
     1814521.509      185182.063     1814590.086      185331.368
     1814660.398       185366.09
#Sta/Elev= 30
       0 1829.86     9.7 1828.87    19.3  1827.9      29 1826.96    38.7 1826.02
    48.3 1825.04      58 1824.04    67.6 1822.97    77.3 1821.66      87 1819.87
    95.2 1818.09   95.591818.006    96.6 1817.79   106.3 1817.36   110.2 1817.85
   111.41818.003     116 1818.59   125.6  1820.2   135.3 1821.57     145 1822.63
   154.6 1823.59   164.3 1824.58   174.1  1825.5   183.9 1826.26   193.7  1826.6
   203.5 1826.95   213.3 1827.88   223.1 1829.19   232.9 1830.47   242.7 1831.69
#Mann= 3 ,-1 , 0
       0     .12       0   95.59    .045       0   111.4     .12       0
Bank Sta=95.59,111.4
XS Rating Curve= 0 ,0
Exp/Cntr=0.3,0.1

Type RM Length L Ch R = 1 ,1292.3  ,101.1,100.7,100.4
XS GIS Cut Line= 3
     1814449.461      185227.202     1814526.718      185376.507
     1814615.259      185401.681
#Sta/Elev= 24
       0 1822.72     9.3 1821.31    18.7    1820      28 1818.79    37.4 1817.69
    46.7 1816.78    65.4 1815.22   87.98 1813.07    93.4 1812.62   102.7 1812.53
  108.051813.104   112.1 1813.54   121.4 1815.28   130.8 1817.26   149.4 1820.98
   158.8 1822.73   168.1 1824.23   177.3 1825.02   186.5 1825.24   214.1 1825.06
   232.5 1825.19   241.8 1825.45     251 1825.97   260.2 1826.67
#Mann= 3 ,-1 , 0
       0     .12       0   87.98    .045       0  108.05     .12       0
Bank Sta=87.98,108.05
XS Rating Curve= 0 ,0
Exp/Cntr=0.3,0.1

Type RM Length L Ch R = 1 ,1191.6  ,150.1,129.6,108.7
XS GIS Cut Line= 4
     1814320.988      185286.229     1814376.544      185307.063
     1814462.481      185466.785     1814509.582      185479.072
#Sta/Elev= 29
       0 1833.59     8.5  1829.8      17 1825.86    25.4 1822.07    33.9 1818.62
    42.4  1815.7    50.9 1813.68    59.3 1812.71    68.9 1812.18    97.5 1812.04
  110.421811.551   116.6 1811.26   124.81811.559   126.2 1811.61   135.7 1813.38
   154.8 1818.95   164.3 1821.34   173.9 1823.11   183.4 1824.25     193  1824.9
   202.5 1825.15   212.1 1825.07   221.6 1824.61   231.2 1823.85   240.7 1822.96
   250.4 1822.53   260.2 1822.54   279.6 1822.97   289.4 1823.27
#Mann= 3 ,-1 , 0
       0     .12       0  110.42    .045       0   124.8     .12       0
#XS Ineff= 2 , 0
           91.02 1815.41
Permanent Ineff=
       F       F
Bank Sta=110.42,124.8
XS Rating Curve= 0 ,0
Exp/Cntr=0.3,0.1

Type RM Length L Ch R = 1 ,1062    ,125.3,131.1,137.1
XS GIS Cut Line= 2
     1814252.412      185452.028     1814496.232      185494.178
#Sta/Elev= 25
       0 1825.57     9.5 1821.64      19 1818.42    28.6 1815.82    38.1  1813.6
    47.6 1812.02    66.6 1809.58    76.1 1808.23   84.081806.962    85.6 1806.72
    95.2 1806.04  100.341806.968   104.7 1807.76   114.2 1811.61   123.7  1815.6
   133.2 1818.28   152.3 1822.12   161.8 1823.72   171.3 1824.21   180.8 1823.72
   199.8 1822.18   209.4 1821.63   218.9  1821.6   237.9 1822.08   247.4 1822.41
#Mann= 3 ,-1 , 0
       0     .12       0   84.08    .045       0  100.34     .12       0
Bank Sta=84.08,100.34
XS Rating Curve= 0 ,0
Exp/Cntr=0.3,0.1