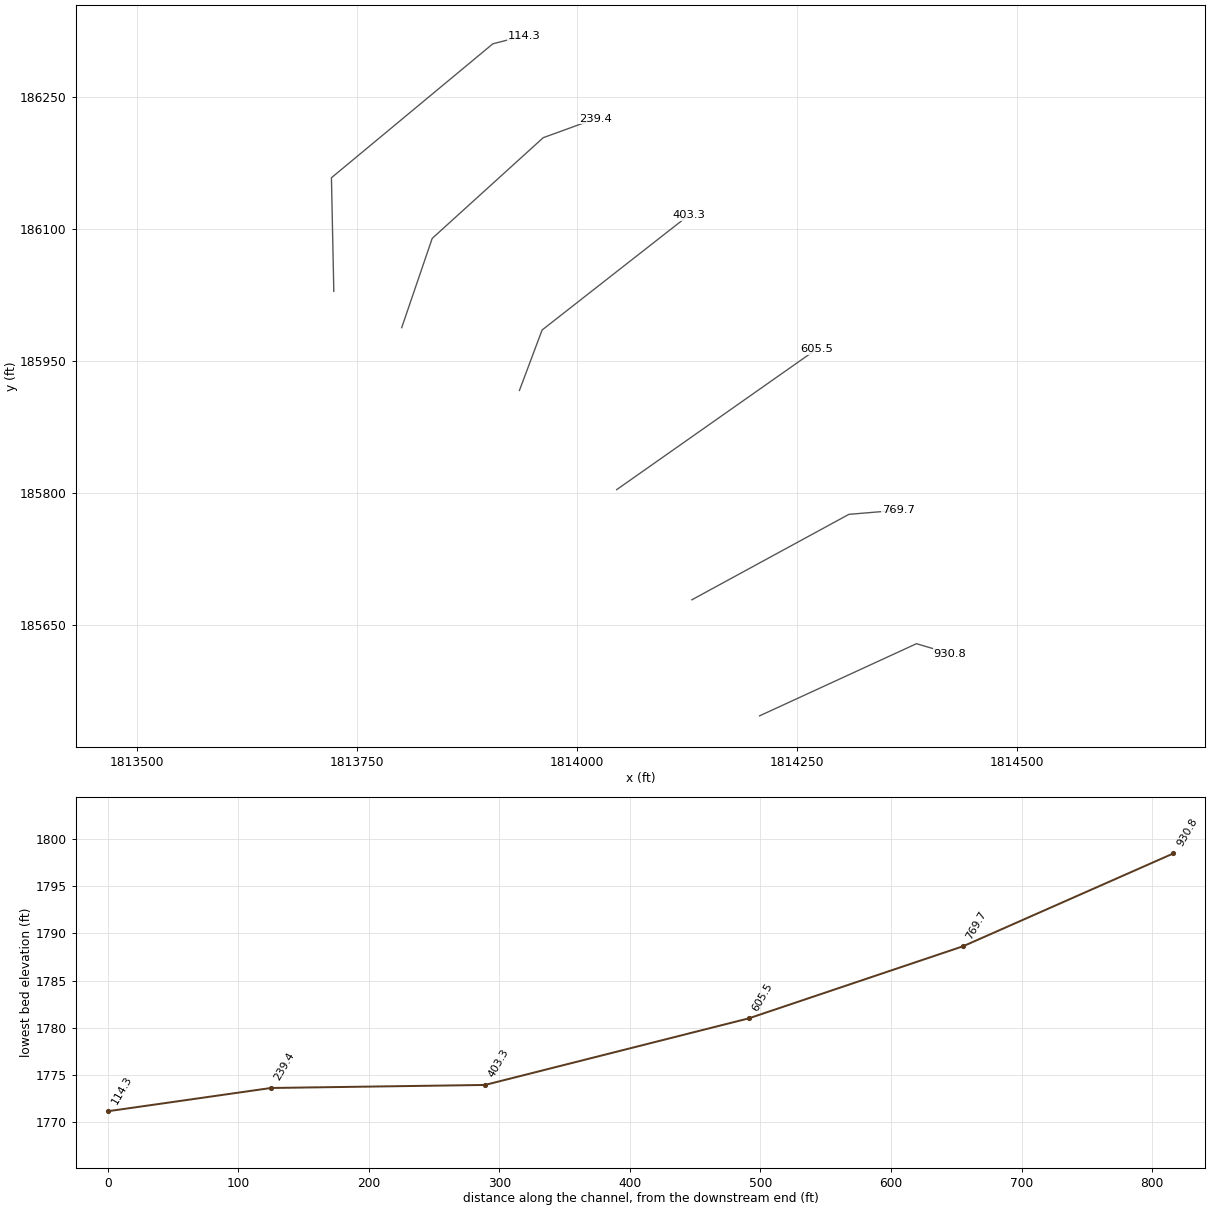
HEC-RAS study HANGINGRN.prj: HANGINGRN

--- HANGINGRN.g01 (geometry) --- (continued)

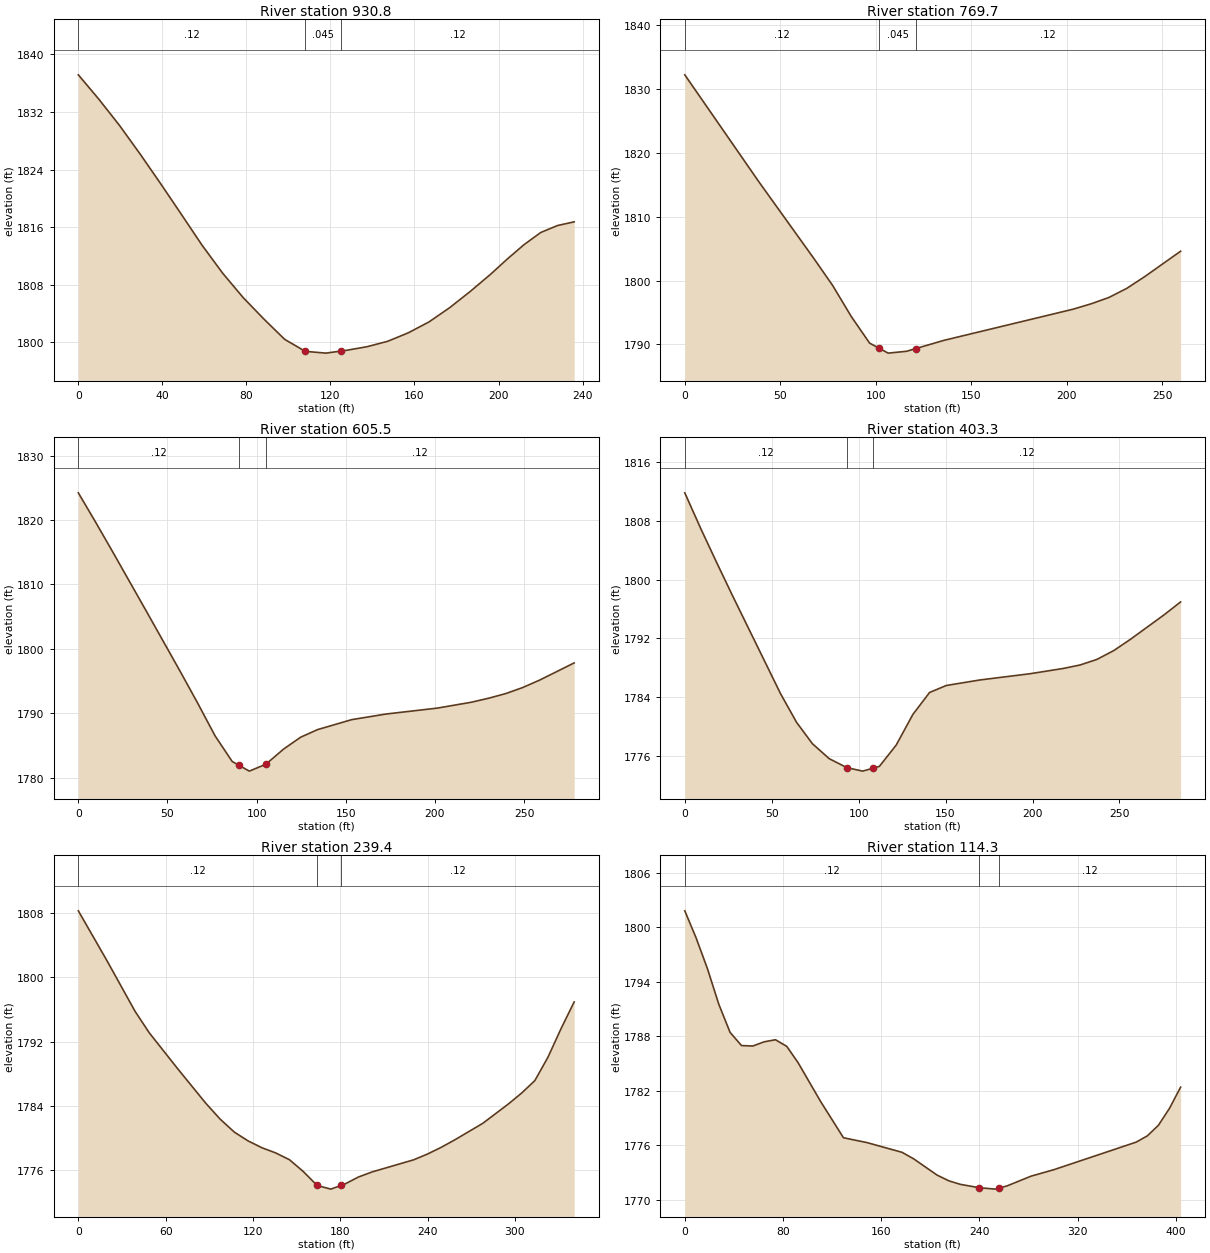
Type RM Length L Ch R = 1 ,930.8   ,159.7,161.1,162.7
XS GIS Cut Line= 3
     1814207.707      185546.212     1814386.093      185628.243
     1814424.119      185617.008
#Sta/Elev= 29
       0 1837.17     9.8 1833.77    19.6 1830.13    29.4 1826.16    39.3 1821.98
    49.1 1817.74    58.9 1813.47    68.7 1809.58    78.5 1806.17    88.4 1803.18
    98.2 1800.38   103.6 1799.46     108 1798.71   117.8 1798.46   118.6 1798.49
  124.981798.745   127.6 1798.85   137.4 1799.35   147.3 1800.11   157.1 1801.29
   166.9  1802.8   176.7 1804.77   186.5 1807.03   196.3 1809.45   204.3 1811.58
   212.2 1813.56   220.1 1815.24   228.1 1816.21     236 1816.72
#Mann= 3 ,-1 , 0
       0     .12       0     108    .045       0  124.98     .12       0
Bank Sta=108,124.98
XS Rating Curve= 0 ,0
Exp/Cntr=0.3,0.1

Type RM Length L Ch R = 1 ,769.7   ,161.4,164.2,166.6
XS GIS Cut Line= 3
     1814130.647      185678.169      1814309.27      185775.379
     1814365.378      185780.054
#Sta/Elev= 17
       0 1832.22    38.7 1815.51    67.8 1803.38    77.5 1799.21    87.2 1794.37
    96.8 1790.21  101.961789.376   106.5 1788.64   116.2 1788.93  120.931789.349
   135.6 1790.63   203.4 1795.52   212.8 1796.36   222.1 1797.35   231.5 1798.78
   240.9 1800.62   259.7  1804.6
#Mann= 3 ,-1 , 0
       0     .12       0  101.96    .045       0  120.93     .12       0
Bank Sta=101.96,120.93
XS Rating Curve= 0 ,0
Exp/Cntr=0.3,0.1

Type RM Length L Ch R = 1 ,605.5   ,200.9,202.2,203.1
XS GIS Cut Line= 2
     1814045.164      185803.473      1814272.71      185963.371
#Sta/Elev= 23
       0 1824.24     9.6 1819.73    19.2 1815.11    38.4 1805.73    57.5 1796.32
    67.1 1791.49    76.7 1786.49    86.3 1782.51    90.2  1781.9    95.9 1781.01
   105.2 1782.08   115.1 1784.43   124.7 1786.28   134.3 1787.47   153.4 1789.01
   172.6 1789.88   201.4  1790.8   220.6 1791.72   230.2 1792.34   239.8 1793.06
   249.3    1794   258.9 1795.17   278.1 1797.82
#Mann= 3 ,-1 , 0
       0     .12       0    90.2    .045       0   105.2     .12       0
Bank Sta=90.2,105.2
XS Rating Curve= 0 ,0
Exp/Cntr=0.3,0.1

Type RM Length L Ch R = 1 ,403.3   ,162.2,163.9,165.6
XS GIS Cut Line= 3
     1813934.526      185916.254     1813960.311      185985.014
     1814127.054      186115.509
#Sta/Elev= 25
       0 1811.79     9.2 1806.92    18.4 1802.28    27.5 1797.79    55.1 1784.48
    64.3 1780.59    73.4 1777.69    83.1 1775.65    93.2 1774.44   102.3 1773.96
   108.2 1774.35   111.9  1774.6   121.6  1777.5   131.2 1781.67   140.8 1784.65
   150.4  1785.6   169.7 1786.35   198.6  1787.2   217.8 1787.92   227.4 1788.39
     237 1789.14   246.7 1790.34   256.3 1791.87   275.6 1795.19   285.2 1796.96
#Mann= 3 ,-1 , 0
       0     .12       0    93.2    .045       0   108.2     .12       0
Bank Sta=93.2,108.2
XS Rating Curve= 0 ,0
Exp/Cntr=0.3,0.1

Type RM Length L Ch R = 1 ,239.4   ,125.9,125,124.3
XS GIS Cut Line= 4
     1813800.647      185987.724     1813835.311      186089.181
     1813961.613      186203.764     1814020.762      186225.229
#Sta/Elev= 30
       0  1808.3    19.5 1802.15      39 1795.78    48.7 1793.12    68.2 1788.65
    87.7 1784.31    97.5 1782.35   107.2 1780.74   116.7 1779.64   126.2 1778.79
   135.6 1778.15   145.1  1777.3   154.6 1775.83   164.1  1774.1   173.5 1773.64
  180.481774.094     183 1774.26   192.5 1775.15     202 1775.79   230.4 1777.29
   239.8    1778   249.3 1778.84   258.8 1779.79   277.8 1781.82   295.7 1784.27
   304.7 1785.62   313.7 1787.16   322.7 1790.07   331.7 1793.63   340.7 1796.95
#Mann= 3 ,-1 , 0
       0     .12       0   164.1    .045       0  180.48     .12       0
Bank Sta=164.1,180.48
XS Rating Curve= 0 ,0
Exp/Cntr=0.3,0.1

Type RM Length L Ch R = 1 ,114.3   ,111.1,114.3,117.4
XS GIS Cut Line= 4
      1813723.42       186028.95     1813720.728      186158.191
     1813904.322      186310.535     1813939.369      186319.538
#Sta/Elev= 30
       0 1801.79     9.2 1798.82    18.5 1795.41    27.7 1791.52    36.9 1788.42
    46.2 1786.97    55.4 1786.92    64.6 1787.38    73.9 1787.61    83.1 1786.88
    92.3 1785.09   110.8 1780.79   129.3 1776.83   148.4  1776.3     177 1775.23
   186.5 1774.51   205.6 1772.72   215.2 1772.09   224.7  1771.7  239.981771.334
   253.3 1771.18  255.911771.282   262.9 1771.55     282  1772.6     301 1773.33
   367.8 1776.35   376.9 1777.04   385.9  1778.2     395 1780.08     404  1782.4
#Mann= 3 ,-1 , 0
       0     .12       0  239.98    .045       0  255.91     .12       0
Bank Sta=239.98,255.91
XS Rating Curve= 0 ,0
Exp/Cntr=0.3,0.1

Chan Stop Cuts=-1
Use User Specified Reach Order=0
Composite Channel Slope=5